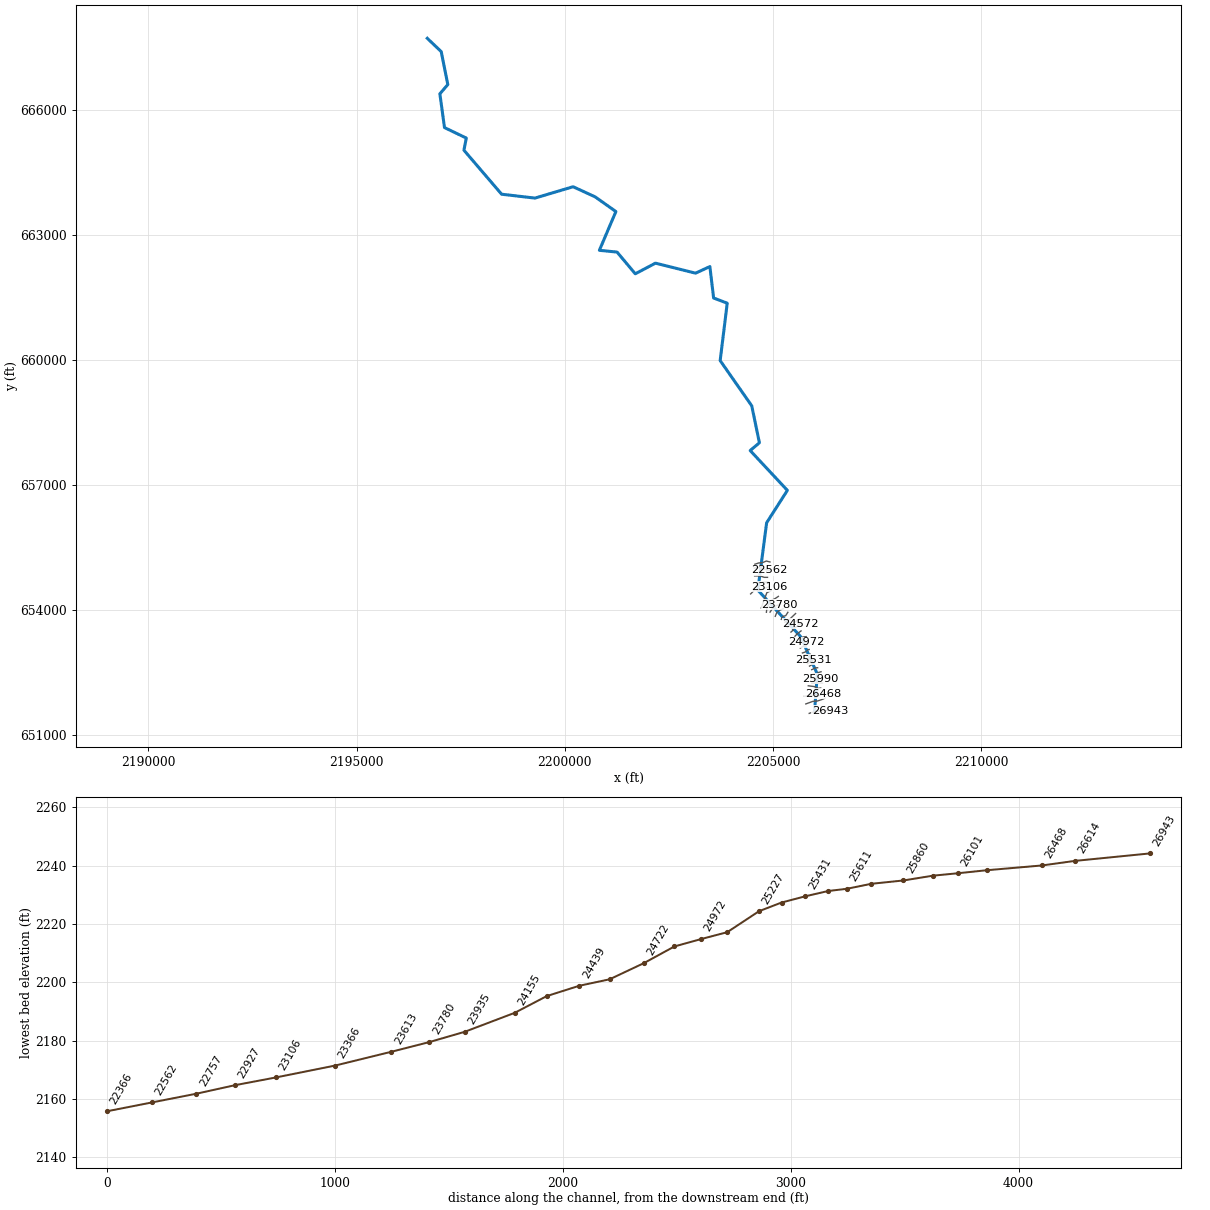
--- PANTHERCK.prj (project) ---

Proj Title=PANTHERCK
Current Plan=p01
Default Exp/Contr=0,0
English Units
Geom File=g01
Flow File=f01
Plan File=p01
BEGIN DESCRIPTION:
---------- MODELED AS PART OF WVEMD CTP PROGRAM, 2023----------
Stream Name: Panther Creek
Flood Zone:  AFH
Upshur County, WV
HEC-RAS Version: RAS 6.3
Vertical Datum: NAVD88
Projection: NAD 1983 StatePlane West Virginia S FIPS 4702 (US Feet)
Terrain: 1-meter LIDAR (FEMA Region III 3DEP collected 2016-2018)
Land Use: 2019 NLCD
Hydrologic Method:
WV SIR2010-5033 regression equations
Additional Model Notes:
None
END DESCRIPTION:
DSS File=dss
DSS Export Rating Curves= 0
DSS Export Rating Curve Sorted= 0
DSS Export Volume Flow Curves= 0
DXF OffsetX= 0
DXF OffsetY= 0
DXF ScaleX= 0
DXF ScaleY= 0

--- PANTHERCK.p01 (plan) ---

Plan Title=Floodplain
Program Version=6.30
Short Identifier=Floodplain
Geom File=g01
Flow File=f01
Subcritical Flow
K Sum by GR= 0
Std Step Tol= 0.01
Critical Tol= 0.01
Num of Std Step Trials= 20
Max Error Tol= 0.3
Flow Tol Ratio= 0.001
Split Flow NTrial= 30
Split Flow Tol= 0.02
Split Flow Ratio= 0.02
Log Output Level= 0
Friction Slope Method= 1
Unsteady Friction Slope Method= 2
Unsteady Bridges Friction Slope Method= 1
Parabolic Critical Depth
Global Vel Dist= 0 , 0 , 0
Global Log Level= 0
CheckData=False
Encroach Param=-1 ,0,0, 0
Computation Interval=0.1SEC
Output Interval=1SEC
Instantaneous Interval=Max Profile
Mapping Interval=1HOUR
Computation Time Step Use Courant=        0
Computation Time Step Use Time Series=    0
Computation Time Step Count To Double=0
Computation Time Step Max Doubling=0
Computation Time Step Max Halving=0
Computation Time Step Residence Courant=0
Run HTab= 0
Run UNet= 0
Run Sediment= 0
Run PostProcess= 0
Run WQNet= 0
Run RASMapper=-1
UNET Theta= 0
UNET Theta Warmup= 0
UNET ZTol= 0
UNET ZSATol= 0
UNET MxIter= 0
UNET Max Iter WO Improvement= 0
UNET MaxInSteps= 0
UNET DtIC= 0
UNET DtMin= 0
UNET MaxCRTS= 0
UNET WFStab= 0
UNET SFStab= 0
UNET WFX= 1
UNET SFX= 1
UNET Gravity=32.17405
UNET 1D Methodology=Finite Difference
UNET DSS MLevel= 1
UNET Pardiso=0
UNET DZMax Abort= 0
UNET Use Existing IB Tables= 0
UNET Froude Reduction=False
UNET Froude Limit= 0
UNET Froude Power= 0
UNET D1 Cores= 0
UNET WindReference=Eulerian
UNET WindDragFormulation=Hsu (1988)
UNET D2 Coriolis=0
UNET D2 Cores= 0
UNET D2 Theta= 1
UNET D2 Theta Warmup= 1
UNET D2 Z Tol= 0.01
UNET D2 Volume Tol= 0.01
UNET D2 Max Iterations= 20
UNET D2 Equation= 0
UNET D2 RampUpFraction=0.1
UNET D2 TimeSlices= 1
UNET D2 Turbulence Formulation=Non-Conservative (original)
UNET D2 Eddy Viscosity=0.3
UNET D2 Transverse Eddy Viscosity=0.1
UNET D2 Smagorinsky Mixing=0
UNET D2 BCVolumeCheck=0
UNET D2 Cores=0
UNET D2 SolverType=PARDISO (Direct)
UNET D2 Minimum Iterations= 3
UNET D2 Maximum Iterations= 30
UNET D2 Restart Number= 10
UNET D2 Relaxation Coeff=1.3
UNET D2 SOR Precondition Iterations= 10
UNET D2 ILUT Maximum Fill= 8
UNET D2 ILUT Tolerance=1E-08
UNET D2 Convergence Tolerance=0.00001
UNET D1D2 MaxIter= 0
UNET D1D2 ZTol=0.01
UNET D1D2 QTol=0.1
UNET D1D2 MinQTol=1
DSS File=dss
Write IC File= 0
Write IC File at Fixed DateTime=0
Write IC File at Sim End=0
Echo Input=False
Echo Parameters=False
Echo Output=False
Write Detailed= 0
HDF Write Warmup=0
HDF Write Time Slices=0
HDF Flush=0
HDF Compression= 1
HDF Chunk Size= 1
HDF Spatial Parts= 1
HDF Use Max Rows=0
HDF Fixed Rows= 1
Calibration Method= 0
Calibration Iterations= 20
Calibration Max Change=0.05
Calibration Tolerance=0.2
Calibration Maximum=1.5
Calibration Minimum=0.5
Calibration Optimization Method= 1
WQ AD Non Conservative
WQ ULTIMATE=-1
WQ Max Comp Step=1HOUR
WQ Output Interval=15MIN
WQ Output Selected Increments= 0
WQ Output face flow=0
WQ Output face velocity=0
WQ Output face area=0
WQ Output face dispersion=0
WQ Output cell volume=0
WQ Output cell surface area=0
WQ Output cell continuity=0
WQ Output cumulative cell continuity=0
WQ Output face conc=0
WQ Output face dconc_dx=0
WQ Output face courant=0
WQ Output face peclet=0
WQ Output face adv mass=0
WQ Output face disp mass=0
WQ Output cell mass=0
WQ Output cell source sink temp=0
WQ Output nsm pathways=0
WQ Output nsm derived pathways=0
WQ Create Restart=0
WQ Fixed Restart=0
WQ System Summary=0
WQ Write To DSS=0
Sorting and Armoring Iterations= 10
XS Update Threshold= 0.02
Bed Roughness Predictor= 0
Hydraulics Update Threshold= 0.02
Energy Slope Method= 1
Volume Change Method= 1
Sediment Retention Method= 0
Sediment TS Multiplier= 1
Warm Up Method= 0
XS Weighting Method= 0
Number of US Weighted Cross Sections= 1
Number of DS Weighted Cross Sections= 1
Upstream XS Weight=0
Main XS Weight=1
Downstream XS Weight=0
Number of DS XS's Weighted with US Boundary= 1
Upstream Boundary Weight= 1
Weight of XSs Associated with US Boundary= 0
Number of US XS's Weighted with DS Boundary= 1
Downstream Boundary Weight= 0.5
Weight of XSs Associated with DS Boundary= 0.5
Percentile Method= 0
Sediment Output Level= 3
Mass or Volume Output= 0
Output Increment Type= 1
Profile and TS Output Increment= 1
Transport Output Increment 1
XS Output Flag= 0
XS Output Increment= 10
Read HDF5 Sediment Hotstart= 0
Sediment Hotstart Type= 0
Write Gradation File= 0
Read Gradation Hotstart= 0
Write HDF5 File= 1
Write Binary Output= 1
Write DSS Sediment File= 0
DSS Sediment Output Type= 1
SV Curve= 0
Specific Gage Flag= 0
Subcell Erosion Methods= 0
Subcell Deposition Methods= 0
Advection Scheme= 1
Matrix Solver= 0
Implicit Weighting Factor= 1
Maximum Outer Loop Convergence Iterations= 5
Convergence Maximum Absolute= 0.001
Convergence RMSE= 0.0001
Grain Fractions Max Abs Error= 0.001
Max Subgrid Regions= 1
Max Subgrid Length Scale= 3.402823E+38
Initial Layer Thickness= 3.402823E+38
Min Layer Thickness= 3.402823E+38
Max Layer Thickness= 3.402823E+38
Number of Layers= 5

--- PANTHERCK.f01 (steady flow) ---

Flow Title=Flows
Program Version=6.30
Number of Profiles= 1
Profile Names=01pct
River Rch & RM=PANTHERCK,Main,26943
     325
River Rch & RM=PANTHERCK,Main,26101
     364
River Rch & RM=PANTHERCK,Main,23613
     432
River Rch & RM=PANTHERCK,Main,20217
     533
River Rch & RM=PANTHERCK,Main,18989
     598
River Rch & RM=PANTHERCK,Main,16537
     814
River Rch & RM=PANTHERCK,Main,12998
     918
River Rch & RM=PANTHERCK,Main,8370
    1030
River Rch & RM=PANTHERCK,Main,6590
    1150
Boundary for River Rch & Prof#=PANTHERCK,Main            , 1
Up Type= 0
Dn Type= 3
Dn Slope=0.0337
DSS Import GetInterval= 0
DSS Import GetPeak= 0
DSS Import FillOption= 0

--- PANTHERCK.g01 (geometry) ---

Geom Title=Geometry
Program Version=6.31

River Reach=PANTHERCK       ,Main
Reach XY= 30
     2205991.521      651542.348     2206059.685      652452.693
2205656.41244079653356.0642206372204631.81704485654468.975156904
     2204842.974      656084.313     2205340.584       656862.85
     2204448.382      657818.437     2204669.444      658005.388
     2204485.641      658892.067     2203727.593      659977.716
     2203897.002       661354.65     2203570.603      661479.475
     2203480.462      662233.803     2203136.722      662075.812
     2202174.381      662316.018     2201689.848      662060.931
     2201253.134      662581.492     2200828.667       662624.76
     2201224.832      663554.592     2200726.592      663907.432
     2200198.105      664150.357      2199282.38      663877.843
     2198481.551      663970.904     2197577.473      665027.392
     2197634.448      665318.707     2197111.083      665570.445
     2196999.823      666380.547     2197190.436      666603.096
     2197032.131      667394.082     2196697.891      667712.325

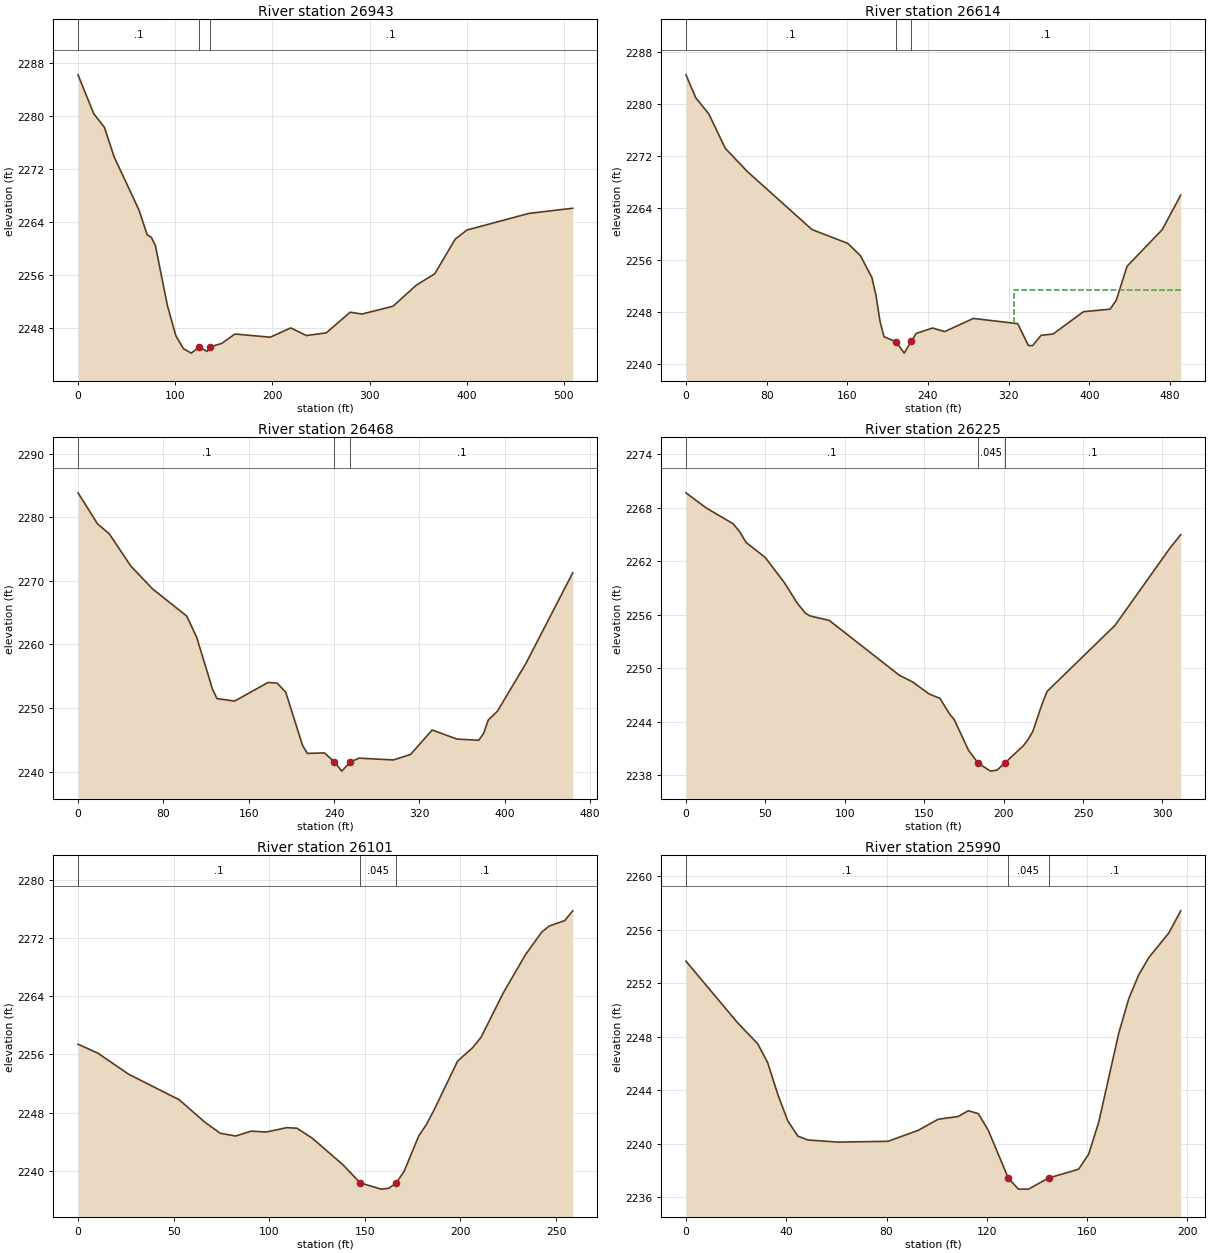
Type RM Length L Ch R = 1 ,26943   ,319.9,329,322.8
XS GIS Cut Line= 4
2205864.88197661651509.9887780182205943.15085733651536.966562439
 2206143.7454215651579.2358247162206365.06952368651576.658644248
#Sta/Elev= 30
       0 2286.19    16.2 2280.33    27.1 2278.29    37.3 2273.78    62.7 2265.82
    71.2 2262.07    75.4  2261.7    79.6 2260.46      92 2251.41   100.7 2246.86
   108.4 2244.92   116.5 2244.24   124.7 2245.14   132.9  2244.5  135.52 2245.16
     148 2245.71   161.5 2247.12   197.8 2246.64   218.9 2248.04   235.1 2246.89
   255.5  2247.3   280.1 2250.41   292.2 2250.13   324.2 2251.31   348.2 2254.49
   367.1  2256.2   388.2 2261.43   400.2 2262.79   464.2 2265.31   509.1 2266.08
#Mann= 3 ,-1,0
       0      .1       0   124.7    .045       0  135.52      .1       0
Bank Sta=124.7,135.52
XS Rating Curve= 0 ,0
Exp/Cntr(USF)=0,0
Exp/Cntr=0.3,0.1

Type RM Length L Ch R = 1 ,26614   ,146.5,146.3,144
XS GIS Cut Line= 5
2205782.98186691651736.2807499822205954.00620818651799.242894844
2206045.95189738651802.376939394 2206169.0694078651841.808961679
2206248.86640354651876.546178953
#Sta/Elev= 30
       0 2284.46     9.8 2280.91    22.6 2278.46      39 2273.16    60.9 2269.59
   124.9 2260.68   160.5 2258.55     173 2256.66   184.4 2253.29   188.4 2250.59
   192.4 2246.59   196.4  2244.2   208.4 2243.42   216.4 2241.68  223.29 2243.48
   228.4 2244.71   244.5 2245.54   256.5 2244.99     285 2247.01     329 2246.21
   339.6 2242.85   343.8 2242.84   352.2 2244.42   364.1 2244.62   394.2 2248.05
   420.6 2248.44   426.7  2249.8   437.4 2255.03   472.3 2260.66   490.6 2265.96
#Mann= 3 ,-1,0
       0      .1       0   208.4    .045       0  223.29      .1       0
#XS Ineff= 2 , 0
                          325.28         2251.36
Permanent Ineff=
       F       F
Bank Sta=208.4,223.29
XS Rating Curve= 0 ,0
Exp/Cntr(USF)=0,0
Exp/Cntr=0.3,0.1

Type RM Length L Ch R = 1 ,26468   ,241.2,242.7,236.5
XS GIS Cut Line= 4
2205751.11218644651921.5501947622205943.72617981651946.828987019
2206083.69127775651928.7240489772206199.75794264651983.444647779
#Sta/Elev= 30
       0 2283.83    18.4 2278.93    29.3 2277.39    49.5 2272.32    69.7 2268.76
   101.9 2264.46   111.2 2261.14   126.1 2252.96   130.2  2251.5   146.8 2251.11
   178.1 2254.03   186.6 2253.93   194.7  2252.5   210.4 2244.17   214.9 2242.89
     231 2242.96  240.39 2241.54   247.2  2240.1   255.2 2241.53   263.3 2242.14
   295.6 2241.86   311.7 2242.72   331.9 2246.56   355.2 2245.14   375.7 2244.95
   380.2 2246.05   384.6 2248.14   393.2 2249.53     420 2257.08   463.7 2271.25
#Mann= 3 ,-1,0
       0      .1       0  240.39    .045       0   255.2      .1       0
Bank Sta=240.39,255.2
XS Rating Curve= 0 ,0
Exp/Cntr(USF)=0,0
Exp/Cntr=0.3,0.1

Type RM Length L Ch R = 1 ,26225   ,118.9,124.6,128.2
XS GIS Cut Line= 4
2205842.69252858652171.5651326582205990.44340685652153.111887354
2206076.41177362652108.5356971782206141.15338316652120.210413652
#Sta/Elev= 30
       0 2269.66    12.8 2267.96    29.7 2266.19    33.7 2265.33    37.8 2264.11
    49.9 2262.41      62 2259.58      70 2257.31    75.1 2256.18    78.1 2255.86
    90.2 2255.36   134.5 2249.19   142.6 2248.47   153.1 2247.11   159.9 2246.62
   166.1 2244.83   168.9 2244.25   177.9  2240.8  183.74  2239.4   191.7 2238.46
   195.9 2238.58   200.9 2239.39   212.4  2241.3   215.4    2242   218.4 2242.91
   224.3 2246.02   227.4  2247.4   270.2 2254.81   304.6 2263.43   311.5 2264.96
#Mann= 3 ,-1,0
       0      .1       0  183.74    .045       0   200.9      .1       0
Bank Sta=183.74,200.9
XS Rating Curve= 0 ,0
Exp/Cntr(USF)=0,0
Exp/Cntr=0.3,0.1

Type RM Length L Ch R = 1 ,26101   ,110.3,111.3,110.5
XS GIS Cut Line= 3
2205925.74402651652233.6264175152206124.20162762 652237.83447225
2206184.36572942652235.954344069
#Sta/Elev= 30
       0 2257.42    10.4 2256.18    26.4 2253.29    52.9 2249.76    66.4 2246.65
    74.4 2245.14    82.4 2244.76    90.5 2245.43    98.5 2245.31   109.2 2245.92
   114.5 2245.83   122.5 2244.46   138.5 2240.81  147.62 2238.29   158.5 2237.44
   162.5 2237.56   166.4 2238.28   170.5 2239.88   178.2 2244.78   182.2 2246.36
   186.1  2248.3   198.5 2255.09   206.5 2256.97   210.8 2258.39   222.5 2264.54
     234 2269.76   242.5 2272.87   246.5 2273.72   254.5 2274.45   258.7  2275.8
#Mann= 3 ,-1,0
       0      .1       0  147.62    .045       0   166.4      .1       0
Bank Sta=147.62,166.4
XS Rating Curve= 0 ,0
Exp/Cntr(USF)=0,0
Exp/Cntr=0.3,0.1

Type RM Length L Ch R = 1 ,25990   ,125.3,129.5,134.8
XS GIS Cut Line= 2
2205927.55893592652343.8577521742206124.82833702652344.375069186
#Sta/Elev= 30
       0 2253.65    20.6 2249.04    28.6 2247.47    32.6 2246.05    36.6 2243.69
    40.6  2241.7    44.6 2240.56    48.6 2240.27    60.6 2240.11    80.6 2240.17
    92.6 2240.99   100.6 2241.82   108.6 2242.03   112.6 2242.46   116.6 2242.24
   119.6  2241.3   120.6 2240.98  128.53 2237.42   132.6 2236.59   136.6 2236.59
   144.6 2237.42   156.6 2238.08   160.6 2239.21   164.6 2241.59   172.6 2248.26
   176.6 2250.85   180.6 2252.64   184.6 2253.92   192.6 2255.77   197.3 2257.42
#Mann= 3 ,-1,0
       0      .1       0  128.53    .045       0   144.6      .1       0
Bank Sta=128.53,144.6
XS Rating Curve= 0 ,0
Exp/Cntr(USF)=0,0
Exp/Cntr=0.3,0.1

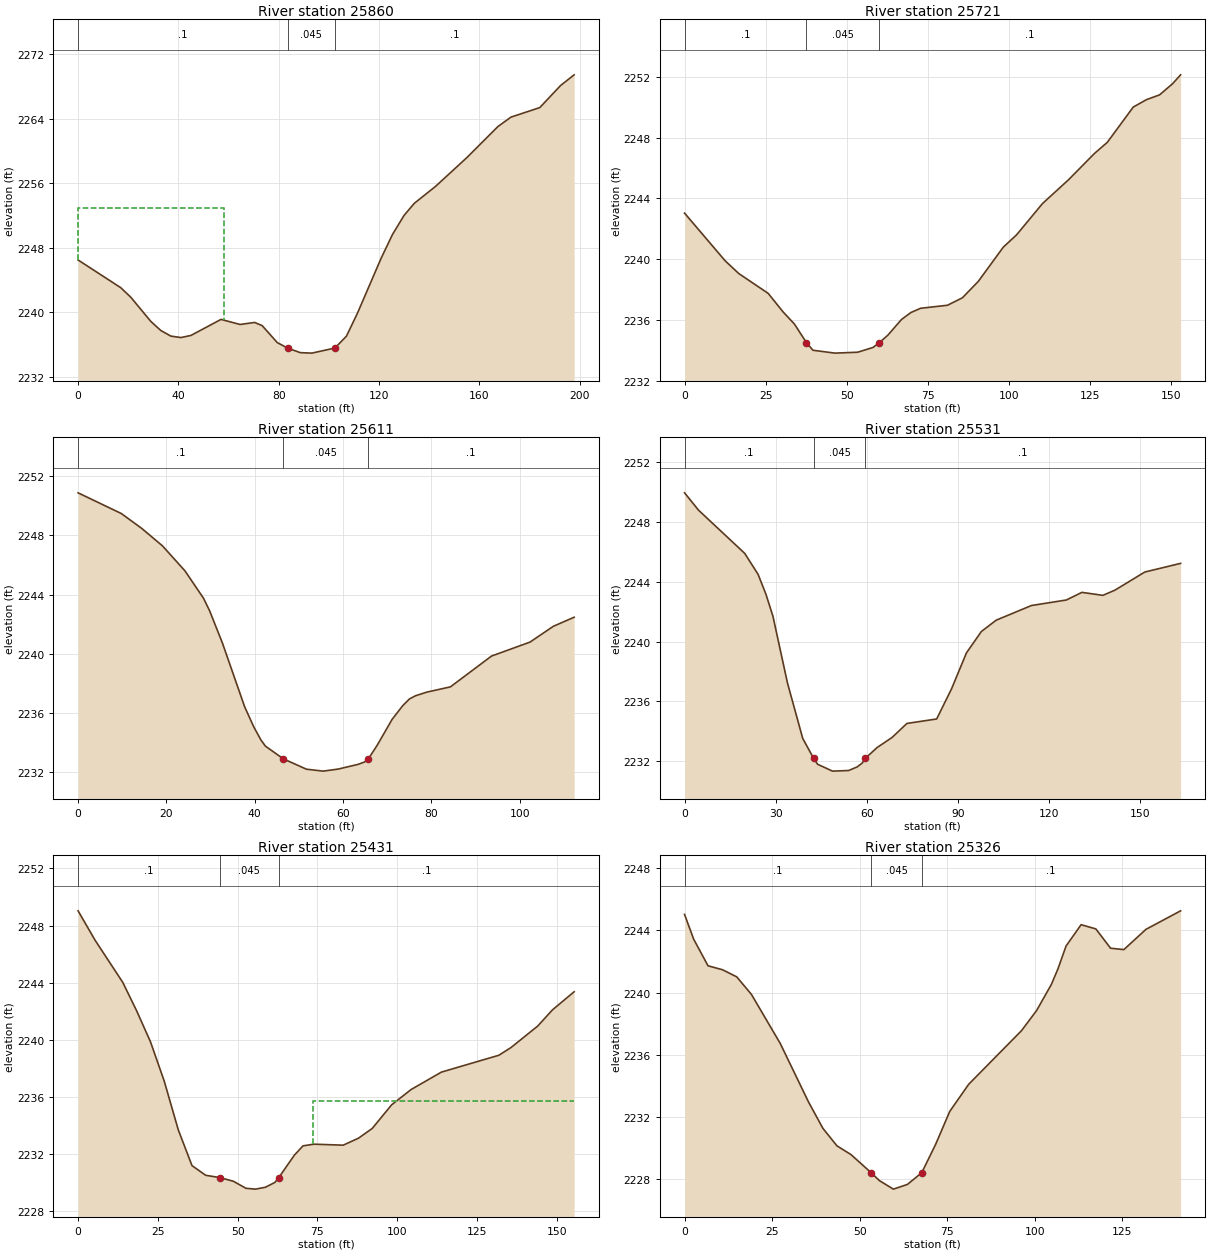
Type RM Length L Ch R = 1 ,25860   ,139.3,139.6,138.5
XS GIS Cut Line= 5
2205963.26311381652455.8906555072205982.06439562652457.770783689
 2206024.6806344652456.517364901 2206084.2180268652490.359672163
2206149.39580375652509.160953975
#Sta/Elev= 30
       0 2246.49      17 2243.06      21 2241.88      29 2238.88      33 2237.75
      37 2237.06      41 2236.88      45 2237.14      57 2239.13    64.6  2238.5
    70.4 2238.75    73.4 2238.36    79.4 2236.26    83.5 2235.58    88.6 2235.01
    93.2 2234.95   102.4 2235.58     107 2237.05   111.4  2239.9   120.8 2246.68
   125.4 2249.67     130 2252.02   134.1 2253.52   142.5  2255.6   154.9 2259.14
   167.4 2263.02   172.6 2264.19   184.1 2265.37   192.4 2268.11   197.8 2269.43
#Mann= 3 ,-1,0
       0      .1       0    83.5    .045       0   102.4      .1       0
#XS Ineff= 2 , 0
           58.14 2252.96
Permanent Ineff=
       F       F
Bank Sta=83.5,102.4
XS Rating Curve= 0 ,0
Exp/Cntr(USF)=0,0
Exp/Cntr=0.3,0.1

Type RM Length L Ch R = 1 ,25721   ,107,109.4,107.8
XS GIS Cut Line= 4
 2205924.4071314652559.2977054752205940.70157563652564.938090018
 2206004.6259338652601.2872348552206066.67016378652605.674200612
#Sta/Elev= 30
       0 2243.03    12.5  2239.9    16.7 2239.06    25.8 2237.75    30.4 2236.53
    33.9 2235.73    37.6 2234.51    39.6 2234.01    46.4 2233.82    53.4 2233.88
    58.1 2234.19   60.09 2234.51    62.7    2235    66.9 2236.03    69.8 2236.49
    72.8 2236.77    81.1 2236.97    85.7 2237.46    90.6 2238.54    98.3 2240.79
   102.4  2241.6   110.4 2243.66   118.4 2245.22   126.4 2246.95   130.4 2247.69
   138.4 2250.01   142.5  2250.5   146.5 2250.81   150.5 2251.54     153 2252.13
#Mann= 3 ,-1,0
       0      .1       0    37.6    .045       0   60.09      .1       0
Bank Sta=37.6,60.09
XS Rating Curve= 0 ,0
Exp/Cntr(USF)=0,0
Exp/Cntr=0.3,0.1

Type RM Length L Ch R = 1 ,25611   ,78.6,80.6,80.6
XS GIS Cut Line= 2
2205871.77808053652644.7681721192205968.22865623652702.300094464
#Sta/Elev= 30
       0 2250.87     9.8 2249.47    14.4 2248.47    19.1 2247.29    24.2  2245.6
    28.4 2243.75    29.8 2242.89    32.7 2240.71    37.7 2236.43    39.8 2235.05
    41.4 2234.18    42.4 2233.77   46.46 2232.91    51.7 2232.21    55.5 2232.08
    58.9 2232.22    63.3 2232.53    64.8 2232.69    65.7  2232.9    67.7 2233.82
    71.1 2235.58    73.5  2236.5      75 2236.95    76.4 2237.17    78.9 2237.41
    84.3 2237.77    93.6 2239.85   102.3 2240.79   107.6 2241.86   112.3 2242.47
#Mann= 3 ,-1,0
       0      .1       0   46.46    .045       0    65.7      .1       0
Bank Sta=46.46,65.7
XS Rating Curve= 0 ,0
Exp/Cntr(USF)=0,0
Exp/Cntr=0.3,0.1

Type RM Length L Ch R = 1 ,25531   ,101.3,100.2,97.5
XS GIS Cut Line= 2
2205824.39885036 652701.736056012205957.82268456652795.950764759
#Sta/Elev= 30
       0 2249.96     4.6  2248.8    19.8 2245.91    24.2 2244.51    26.8 2243.17
    29.1  2241.7    33.9 2237.22    38.9 2233.53    42.5 2232.19    43.8  2231.8
    48.7 2231.34      54 2231.38    56.8 2231.62    58.5 2231.88   59.52  2232.2
    63.4 2232.92    68.3 2233.59    73.2 2234.53      83 2234.83    87.9 2236.85
    92.8 2239.25    97.7 2240.68   102.6 2241.44   114.2 2242.42   125.7 2242.79
   130.8  2243.3   137.7  2243.1   141.7 2243.45   151.5 2244.66   163.3 2245.24
#Mann= 3 ,-1,0
       0      .1       0    42.5    .045       0   59.52      .1       0
Bank Sta=42.5,59.52
XS Rating Curve= 0 ,0
Exp/Cntr(USF)=0,0
Exp/Cntr=0.3,0.1

Type RM Length L Ch R = 1 ,25431   ,107.1,104.6,98.4
XS GIS Cut Line= 2
2205775.32750483652797.0585547982205918.39009534652857.941511007
#Sta/Elev= 30
       0 2249.03     5.3 2246.98      14 2244.02    18.3 2242.05    22.7 2239.85
      27  2237.1    31.4 2233.69    35.7 2231.18      40  2230.5    44.4 2230.34
    48.7 2230.08    52.6 2229.59    55.6 2229.53    58.7 2229.66    61.7    2230
   62.91 2230.34    67.8 2231.91    70.5 2232.56    73.9 2232.68    83.1 2232.61
    87.9  2233.1    92.2 2233.78    98.3 2235.44   104.4 2236.51   113.9 2237.73
   131.9 2238.91   135.7 2239.45   144.1 2240.96   148.7 2242.09   155.5 2243.36
#Mann= 3 ,-1,0
       0      .1       0    44.4    .045       0   62.91      .1       0
#XS Ineff= 2 , 0
                           73.69         2235.72
Permanent Ineff=
       F       F
Bank Sta=44.4,62.91
XS Rating Curve= 0 ,0
Exp/Cntr(USF)=0,0
Exp/Cntr=0.3,0.1

Type RM Length L Ch R = 1 ,25326   ,94.4,99,105.7
XS GIS Cut Line= 4
2205753.68271706652913.2099975522205783.28796746 652920.61131015
2205841.26491614652913.6211815852205891.01818416652930.890910981
#Sta/Elev= 30
       0 2245.02     2.6 2243.43     6.7 2241.72    10.8 2241.47    14.9 2241.01
    19.1 2239.88    27.3 2236.74    35.4 2232.97    39.5 2231.28    43.5 2230.16
    47.5  2229.6   53.34 2228.42    55.6 2227.93    59.6 2227.38    63.6 2227.68
    67.7 2228.43    71.7 2230.27    75.7 2232.37    81.1 2234.11    96.2 2237.56
   100.5 2238.85   104.7 2240.52   106.6 2241.53   108.9 2242.99   113.2 2244.36
   117.4 2244.09   121.6 2242.85   125.4 2242.76   131.7 2244.06   141.6 2245.25
#Mann= 3 ,-1,0
       0      .1       0   53.34    .045       0    67.7      .1       0
Bank Sta=53.34,67.7
XS Rating Curve= 0 ,0
Exp/Cntr(USF)=0,0
Exp/Cntr=0.3,0.1

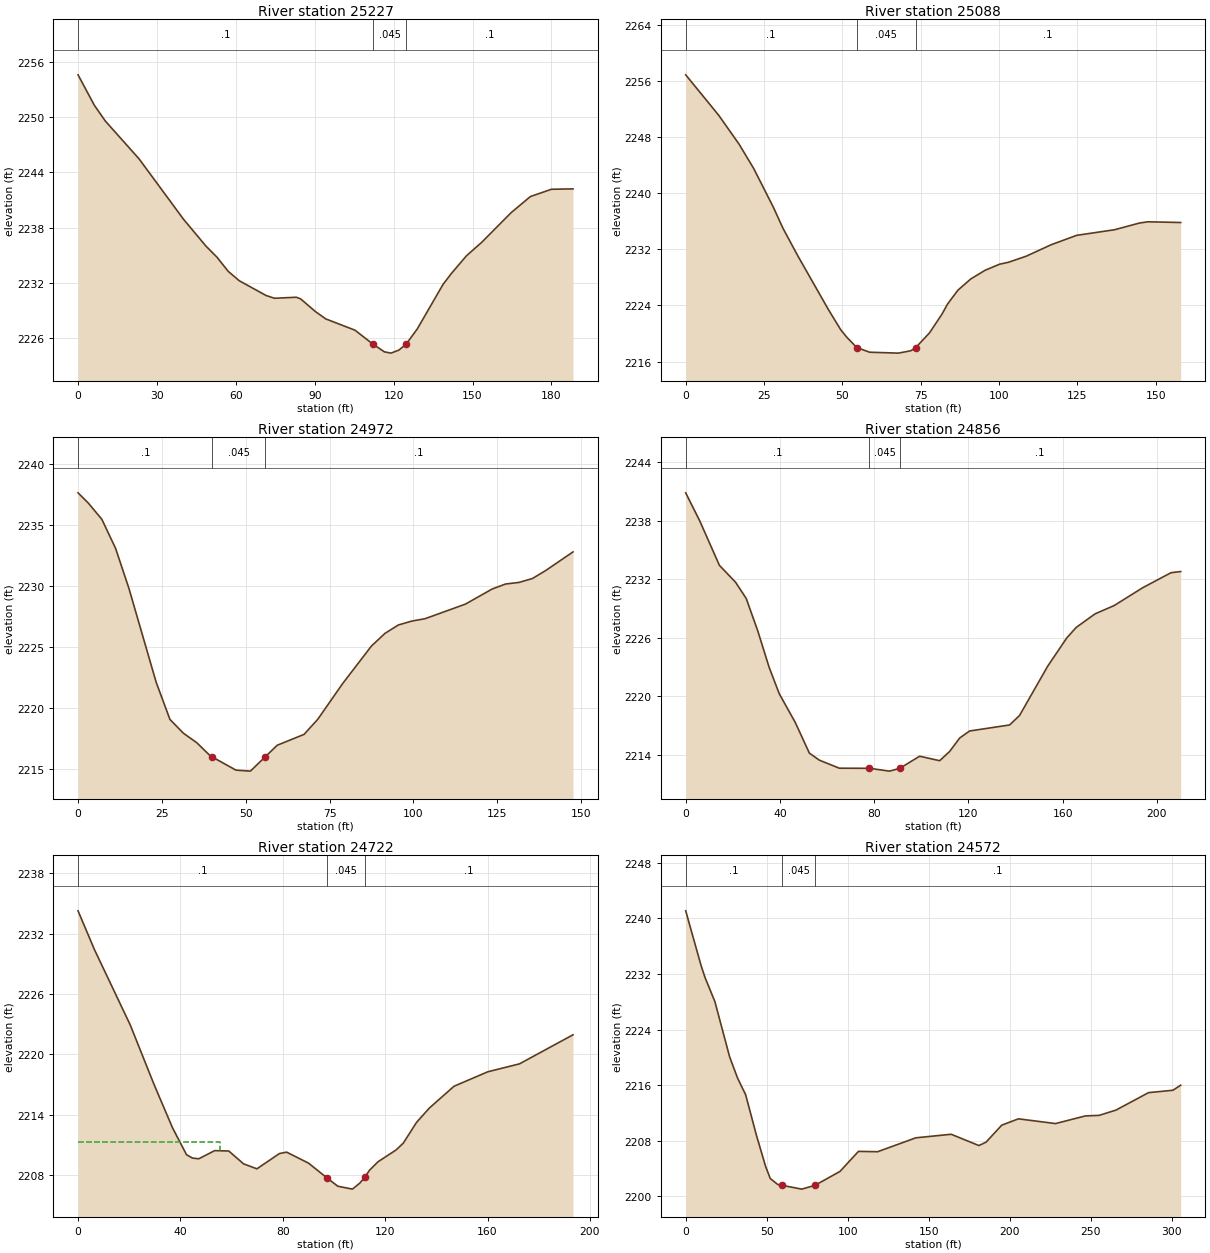
Type RM Length L Ch R = 1 ,25227   ,143.2,139.3,138.3
XS GIS Cut Line= 4
2205702.33485406652959.7392325692205778.83263202 652986.75925608
2205833.04123548653039.443495755  2205864.291222653043.144152054
#Sta/Elev= 30
       0 2254.58     6.2 2251.28    10.4 2249.56    23.2 2245.47    40.1 2238.92
    48.6 2236.02    52.9 2234.78    57.1 2233.27    61.3 2232.25    71.5 2230.65
    74.7 2230.35      83 2230.46    84.6 2230.29    90.3  2228.9    94.2 2228.11
   105.3 2226.89   112.1 2225.38   116.5 2224.54     119  2224.4     122 2224.73
  124.73 2225.36     129 2227.03   138.8 2231.86     142 2233.05   147.7 2234.96
   153.5 2236.42   164.7 2239.64     172 2241.38     180 2242.17   188.2 2242.21
#Mann= 3 ,-1,0
       0      .1       0   112.1    .045       0  124.73      .1       0
Bank Sta=112.1,124.73
XS Rating Curve= 0 ,0
Exp/Cntr(USF)=0,0
Exp/Cntr=0.3,0.1

Type RM Length L Ch R = 1 ,25088   ,120.4,115.2,113.2
XS GIS Cut Line= 4
 2205649.6337609653077.3185612212205678.82782726 653094.99947465
2205739.27188015653129.538933442 2205793.1369885 653135.70669394
#Sta/Elev= 30
       0 2256.86    10.5 2251.12      17 2247.01    21.7 2243.52      28 2237.98
      31 2235.04    35.7 2231.14    45.5 2223.46    49.5 2220.53    51.4 2219.49
    54.6 2218.01    58.7 2217.34    67.9 2217.21    71.9 2217.55   73.44 2218.01
    77.8 2220.08    81.8 2222.76    83.6 2224.21    86.9 2226.18      91 2227.78
    95.6 2229.02   100.2 2229.88     103 2230.15   108.7 2231.02   116.7 2232.66
   124.8 2233.99   136.9 2234.79   144.9 2235.75   147.6 2235.92     158 2235.82
#Mann= 3 ,-1,0
       0      .1       0    54.6    .045       0   73.44      .1       0
Bank Sta=54.6,73.44
XS Rating Curve= 0 ,0
Exp/Cntr(USF)=0,0
Exp/Cntr=0.3,0.1

Type RM Length L Ch R = 1 ,24972   ,113.8,116.7,117.9
XS GIS Cut Line= 4
2205645.11073654653207.6638997562205668.95941046653211.364556055
2205723.64688688653215.0652123542205792.31462043653216.709948487
#Sta/Elev= 30
       0 2237.64     3.1 2236.79     7.1 2235.47    11.2 2233.09    15.2 2229.79
    23.3 2222.12    27.4 2219.08    31.4 2217.95    35.4 2217.17    39.4  2216.1
   40.09 2215.99    47.1 2214.92    51.4 2214.84    55.7 2215.98    59.4 2216.96
    67.4 2217.85    71.5 2219.09    78.9 2222.01    87.5 2225.09    91.5 2226.12
    95.5 2226.81    99.5 2227.13   103.5 2227.33   115.5 2228.52   123.5 2229.76
   127.5 2230.17   131.5  2230.3   135.5 2230.62   139.5 2231.28   147.6  2232.8
#Mann= 3 ,-1,0
       0      .1       0   40.09    .045       0    55.7      .1       0
Bank Sta=40.09,55.7
XS Rating Curve= 0 ,0
Exp/Cntr(USF)=0,0
Exp/Cntr=0.3,0.1

Type RM Length L Ch R = 1 ,24856   ,131.6,134.1,135.6
XS GIS Cut Line= 4
2205595.29968591653288.8482942082205624.08256823 653309.40749587
2205721.94436814653344.7693227282205792.25683783653352.170635326
#Sta/Elev= 30
       0 2240.88       6 2237.98    14.3 2233.44    21.2 2231.69    25.7 2230.03
    30.6  2226.7    35.4 2222.98    39.7 2220.26    46.5 2217.31    52.5 2214.16
    56.7 2213.44    65.2 2212.61      78  2212.6    86.5 2212.31    90.8 2212.59
    99.3 2213.84   107.8 2213.38     112 2214.32   116.3 2215.71   120.5 2216.43
   137.5 2217.05   141.7 2218.02   153.7  2223.1   161.8    2226   165.8 2227.07
   173.8 2228.46   181.9 2229.31     194 2231.14     206 2232.68   210.1  2232.8
#Mann= 3 ,-1,0
       0      .1       0      78    .045       0    90.8      .1       0
Bank Sta=78,90.8
XS Rating Curve= 0 ,0
Exp/Cntr(USF)=0,0
Exp/Cntr=0.3,0.1

Type RM Length L Ch R = 1 ,24722   ,147.7,150.3,151.4
XS GIS Cut Line= 4
2205523.78869091653362.311651909 2205579.2985354653421.152087065
2205627.77713292653458.1586500562205668.85441784653489.244162968
#Sta/Elev= 30
       0 2234.27     6.4 2230.42    20.4 2222.92    29.7    2217    36.9  2212.7
    42.4 2210.01    44.7 2209.68    47.2 2209.61    53.4 2210.42    58.9 2210.38
    64.7  2209.1    69.9 2208.61    78.7 2210.13    81.5 2210.27    90.1 2209.17
    97.1 2207.74   101.5 2206.88   107.2 2206.59   110.1 2207.19  112.04 2207.77
   113.9 2208.47   117.2 2209.31   124.3 2210.49   127.1 2211.17   132.3 2213.24
   137.3 2214.66   146.9 2216.82   160.1 2218.26   172.5 2219.05   193.4 2221.94
#Mann= 3 ,-1,0
       0      .1       0    97.1    .045       0  112.04      .1       0
#XS Ineff= 2 , 0
            55.6 2211.24
Permanent Ineff=
       F       F
Bank Sta=97.1,112.04
XS Rating Curve= 0 ,0
Exp/Cntr(USF)=0,0
Exp/Cntr=0.3,0.1

Type RM Length L Ch R = 1 ,24572   ,135.9,132.8,130
XS GIS Cut Line= 4
2205426.82153955653461.3176992222205451.49258155653480.643348784
 2205502.8905857653550.9558184672205651.93786483 653663.75949061
#Sta/Elev= 30
       0 2241.07     9.4 2233.27    11.9 2231.49      18 2228.02    27.1 2220.07
      32 2217.01      37 2214.61    43.7 2208.73    49.4 2204.24    52.2 2202.56
    56.8 2201.71    59.6 2201.58    71.6 2201.04    79.9  2201.6    95.2 2203.59
   106.6 2206.47   118.4 2206.42     142 2208.42   163.8 2208.93   180.9 2207.31
   185.3 2207.79     195 2210.24   205.3 2211.15   228.2 2210.47   246.6 2211.57
   255.1 2211.65   265.5 2212.41   285.6 2214.92   300.6 2215.26   305.4 2215.99
#Mann= 3 ,-1,0
       0      .1       0    59.6    .045       0    79.9      .1       0
Bank Sta=59.6,79.9
XS Rating Curve= 0 ,0
Exp/Cntr(USF)=0,0
Exp/Cntr=0.3,0.1

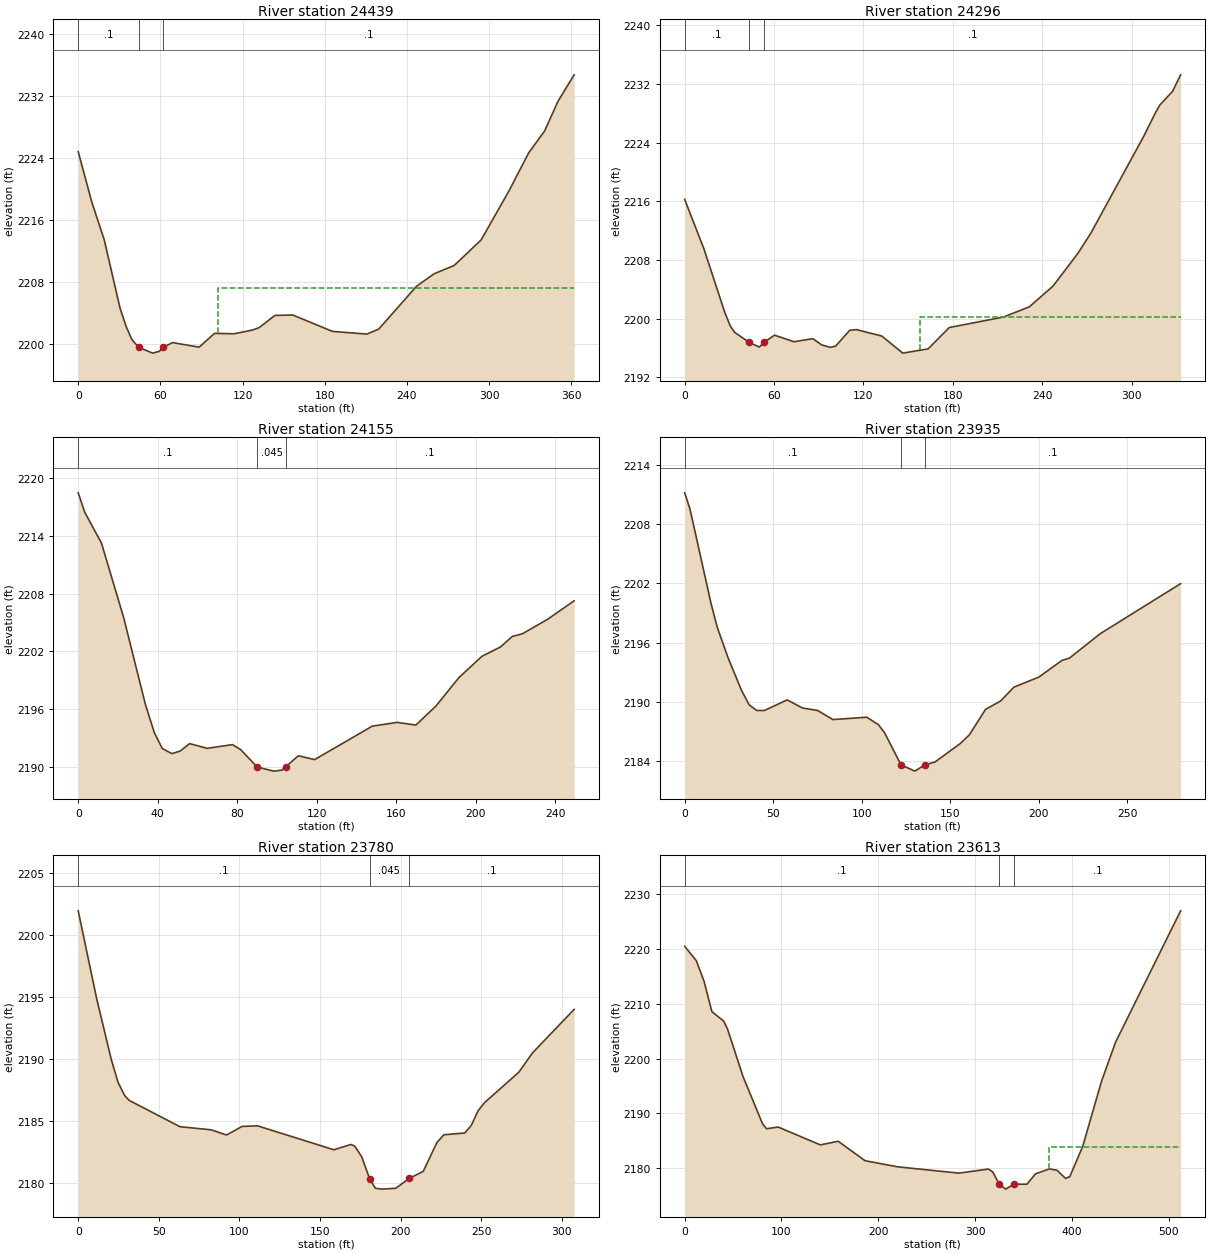
Type RM Length L Ch R = 1 ,24439   ,142.5,142.8,141.4
XS GIS Cut Line= 3
2205339.44061937653571.4845959262205443.39258855653643.087610185
2205635.44771546653780.003944446
#Sta/Elev= 30
       0 2224.84      10 2218.29      19 2213.47    30.5 2204.67    34.9 2202.32
    39.1 2200.61   44.06 2199.59    54.3 2198.83    59.2 2199.06    62.1 2199.59
    68.9 2200.19    88.3  2199.6    99.5 2201.38   113.9 2201.33   127.2 2201.81
   132.1 2202.12   143.6  2203.7   156.7 2203.75   185.6 2201.64   210.7 2201.29
   219.4 2201.93     247 2207.46   259.8 2209.07   274.6 2210.16   294.2 2213.45
   314.7 2219.84     329 2224.72   340.5 2227.51   350.3 2231.35   362.1 2234.77
#Mann= 3 ,-1,0
       0      .1       0   44.06    .045       0    62.1      .1       0
#XS Ineff= 2 , 0
                          102.35         2207.18
Permanent Ineff=
       F       F
Bank Sta=44.06,62.1
XS Rating Curve= 0 ,0
Exp/Cntr(USF)=0,0
Exp/Cntr=0.3,0.1

Type RM Length L Ch R = 1 ,24296   ,143.6,140.9,139.6
XS GIS Cut Line= 3
2205281.16963744653698.2625341272205384.42251689653759.940139112
2205538.12394758653906.835317752
#Sta/Elev= 30
       0 2216.25    12.8 2209.58    26.8 2200.91    30.6 2198.99    33.5 2198.13
    43.2 2196.76    50.1 2196.12   53.44 2196.78    60.3 2197.74    73.4 2196.84
      86 2197.26      92 2196.41    97.7 2196.08   101.3 2196.24   110.7 2198.39
   115.2  2198.5   132.3 2197.62   146.4 2195.29   163.4 2195.87   177.6 2198.78
     214 2200.21   231.3  2201.6   247.2 2204.42   263.8 2208.85   272.6 2211.63
   308.1 2224.84   316.2 2228.15   319.1 2229.16   327.5 2230.99   332.9 2233.24
#Mann= 3 ,-1,0
       0      .1       0    43.2    .045       0   53.44      .1       0
#XS Ineff= 2 , 0
                          158.04         2200.26
Permanent Ineff=
       F       F
Bank Sta=43.2,53.44
XS Rating Curve= 0 ,0
Exp/Cntr(USF)=0,0
Exp/Cntr=0.3,0.1

Type RM Length L Ch R = 1 ,24155   ,212.6,219.7,219.3
XS GIS Cut Line= 4
2205194.28238125653766.6540787582205227.36073877653835.906137528
2205301.44968758653855.2081160942205352.77718693653936.429653523
#Sta/Elev= 30
       0 2218.49     3.3 2216.46    11.7 2213.26      23  2205.4    33.8 2196.47
    38.3 2193.53    42.3 2191.89    47.1 2191.36    51.3 2191.63      56  2192.4
    64.9 2191.91    77.6  2192.3    81.7 2191.78      90 2189.97    98.3 2189.54
   102.4 2189.64  104.36 2189.99   110.7 2191.14   118.9 2190.74   147.9 2194.22
   160.4 2194.61   169.8 2194.33   179.9 2196.31   191.5 2199.28     203 2201.48
   212.4 2202.46   218.3 2203.55   223.4 2203.83   236.1 2205.34   249.4 2207.26
#Mann= 3 ,-1,0
       0      .1       0      90    .045       0  104.36      .1       0
Bank Sta=90,104.36
XS Rating Curve= 0 ,0
Exp/Cntr(USF)=0,0
Exp/Cntr=0.3,0.1

Type RM Length L Ch R = 1 ,23935   ,156.9,155.1,152.2
XS GIS Cut Line= 4
2205050.14219965653839.3208149182205085.70811997653929.784792779
2205163.26026626653988.8852297792205242.22564988654021.035421678
#Sta/Elev= 30
       0 2211.15       3 2209.51    14.9 2199.95    18.4 2197.55    24.6 2194.43
    32.1 2191.18    36.4 2189.72    40.7 2189.15      45 2189.15    57.9 2190.22
    66.5  2189.4    75.1 2189.15    83.7 2188.23   102.8 2188.47   109.4 2187.71
   112.8 2186.92  122.08 2183.67   129.9 2183.02   135.8 2183.67   141.3 2183.94
   155.6 2185.81   160.7 2186.68   169.9 2189.27   178.4 2190.11   185.8  2191.5
     200 2192.53     213 2194.21   217.3 2194.45   234.6 2196.91     280 2201.97
#Mann= 3 ,-1,0
       0      .1       0  122.08    .045       0   135.8      .1       0
Bank Sta=122.08,135.8
XS Rating Curve= 0 ,0
Exp/Cntr(USF)=0,0
Exp/Cntr=0.3,0.1

Type RM Length L Ch R = 1 ,23780   ,165.3,166.9,167.7
XS GIS Cut Line= 4
2204924.86883129653940.6233296582205013.89803302654074.269174038
2205098.50380118654104.727250574 2205152.6514928654122.776481114
#Sta/Elev= 30
       0 2201.92    11.4 2194.87    20.4    2190    24.7  2188.1    28.7 2187.06
    31.6 2186.65    63.1 2184.53    82.4 2184.28      92 2183.86   101.6 2184.55
   111.2  2184.6   158.6 2182.67   169.2  2183.1   171.5 2182.96   175.8 2182.12
  180.72 2180.35   184.3 2179.57   188.5  2179.5     197 2179.57   205.3 2180.36
     214 2180.93   222.5 2183.26   226.8 2183.88   239.7 2184.02   243.8 2184.63
     248 2185.81   251.9 2186.45   273.3 2188.92   281.8 2190.48   307.6 2193.98
#Mann= 3 ,-1,0
       0      .1       0  180.72    .045       0   205.3      .1       0
Bank Sta=180.72,205.3
XS Rating Curve= 0 ,0
Exp/Cntr(USF)=0,0
Exp/Cntr=0.3,0.1

Type RM Length L Ch R = 1 ,23613   ,237.3,246.6,250.8
XS GIS Cut Line= 5
  2204837.463376653937.2150858722204850.11244376654051.130758537
2204947.24878517654218.6833054982205051.99797396654268.518290607
2205124.72721224654318.036069866
#Sta/Elev= 30
       0 2220.52      12  2217.9    20.1 2214.08    28.1 2208.59    40.2 2206.87
    44.2 2205.44    60.3 2196.72    80.5 2188.08    84.5  2187.2    96.6 2187.51
   140.1 2184.25   158.6 2184.91   186.3 2181.36   220.1 2180.24   283.4 2179.09
   313.7 2179.84   318.2 2179.32  324.94 2177.06   331.5 2176.17   340.3 2177.06
   353.6 2177.07   362.5 2178.97   376.9 2179.87   384.6 2179.61   393.5 2178.12
   397.9 2178.47   411.2 2183.99   430.6 2195.86     445 2202.97   512.3    2227
#Mann= 3 ,-1,0
       0      .1       0  324.94    .045       0   340.3      .1       0
#XS Ineff= 2 , 0
                          376.81         2183.85
Permanent Ineff=
       F       F
Bank Sta=324.94,340.3
XS Rating Curve= 0 ,0
Exp/Cntr(USF)=0,0
Exp/Cntr=0.3,0.1

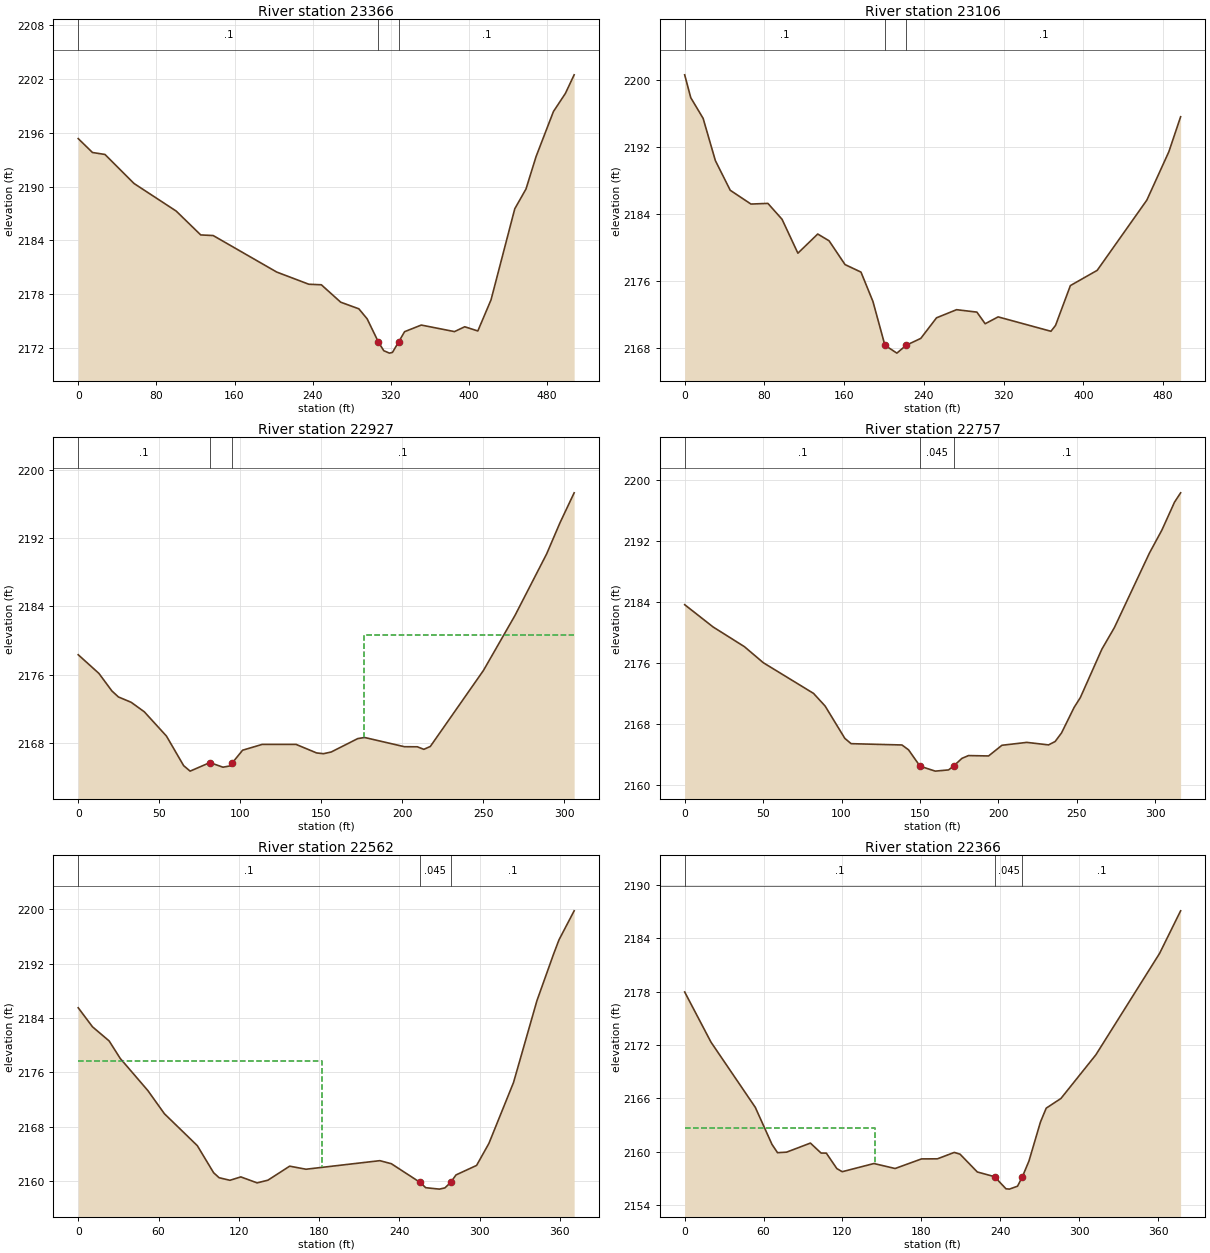
Type RM Length L Ch R = 1 ,23366   ,271.4,260.2,246.9
XS GIS Cut Line= 3
2204713.24157878 654039.423759462204847.44690075654406.054461004
2204952.29882923654458.686017258
#Sta/Elev= 30
       0 2195.36    14.6 2193.81    27.4 2193.59    57.2 2190.35   100.3 2187.28
   125.4 2184.62   138.2 2184.55   203.2 2180.48   236.1 2179.12   248.9 2179.06
   268.7 2177.12   287.3 2176.38   295.8 2175.26   307.3 2172.68   312.8 2171.71
   318.6 2171.44   321.7 2171.52   327.9 2172.66   334.1 2173.83   351.2 2174.57
   385.2 2173.84   395.7 2174.38   409.1 2173.91   422.6 2177.38   446.9 2187.53
   458.4 2189.74   468.7 2193.35   486.5 2198.38   498.7 2200.39   507.7 2202.47
#Mann= 3 ,-1,0
       0      .1       0   307.3    .045       0   327.9      .1       0
Bank Sta=307.3,327.9
XS Rating Curve= 0 ,0
Exp/Cntr(USF)=0,0
Exp/Cntr=0.3,0.1

Type RM Length L Ch R = 1 ,23106   ,180.9,179.7,178
XS GIS Cut Line= 6
2204458.39915079 654376.848877152204552.77934638654471.229072739
2204704.50975436654468.8470960242204749.77209946654481.381283898
2204812.44303884654518.2875037522204900.18235396654548.230285898
#Sta/Elev= 30
       0 2200.61     6.1 2197.88    18.5 2195.41    30.8 2190.36    45.7 2186.82
    66.5 2185.17    83.5 2185.25    97.7 2183.35   113.6  2179.3   133.5 2181.59
   144.9 2180.78   160.9 2177.94   176.9 2177.04   188.9 2173.53   200.9  2168.3
   212.9 2167.36  222.27  2168.3   236.9 2169.12   252.7 2171.58   272.8 2172.55
   293.2 2172.26   301.5 2170.87   314.5 2171.69   367.5 2169.97   372.1 2170.67
     387 2175.43   413.9 2177.25   463.7 2185.64   485.8 2191.42   497.6  2195.6
#Mann= 3 ,-1,0
       0      .1       0   200.9    .045       0  222.27      .1       0
Bank Sta=200.9,222.27
XS Rating Curve= 0 ,0
Exp/Cntr(USF)=0,0
Exp/Cntr=0.3,0.1

Type RM Length L Ch R = 1 ,22927   ,170.6,169.4,168
XS GIS Cut Line= 5
 2204571.4292898654648.1290623382204608.40514403654649.382481126
2204690.50407461654636.8482932512204753.80172338654658.783122032
2204872.87650819   654661.916669
#Sta/Elev= 30
       0 2178.33    12.8 2176.14    20.8 2174.09    24.8 2173.39    32.7 2172.76
    40.8 2171.65    54.5  2168.8    65.1 2165.34    69.1  2164.7    81.3  2165.7
    89.4 2165.16    93.4  2165.3      952165.635   101.5 2167.15   113.6 2167.83
   134.5 2167.83   147.2 2166.83   151.4 2166.74   156.2 2166.94   172.6 2168.51
   176.8 2168.64   201.4 2167.56   209.4 2167.55   213.4 2167.25   217.4 2167.59
   250.2 2176.49   269.7 2182.94   289.2 2190.13   297.4 2193.76   306.2 2197.29
#Mann= 3 ,-1,0
       0      .1       0    81.3    .045       0      95      .1       0
#XS Ineff= 2 , 0
                          176.48         2180.65
Permanent Ineff=
       F       F
Bank Sta=81.3,95
XS Rating Curve= 0 ,0
Exp/Cntr(USF)=0,0
Exp/Cntr=0.3,0.1

Type RM Length L Ch R = 1 ,22757   ,192.9,194.6,192.7
XS GIS Cut Line= 4
2204554.09913085654808.8687820852204685.50787534654810.225225286
2204784.84909916654774.882674504 2204864.1310374654774.882674504
#Sta/Elev= 30
       0 2183.61    18.1 2180.69    38.1  2178.1    50.1    2176    82.1 2171.98
    89.5 2170.32   102.1 2166.07   106.1 2165.38   138.5 2165.21   142.7 2164.57
     150 2162.43   159.7 2161.78   168.2 2161.94  171.36 2162.44   176.7 2163.45
   180.9 2163.82   193.7 2163.77   202.2 2165.17   218.1 2165.55   231.9 2165.22
   236.1 2165.66   240.2 2166.79   248.2 2170.13   252.2 2171.43   265.9 2177.77
   273.9 2180.61   296.2 2190.37   304.2 2193.41   312.2 2197.05   316.1 2198.28
#Mann= 3 ,-1,0
       0      .1       0     150    .045       0  171.36      .1       0
Bank Sta=150,171.36
XS Rating Curve= 0 ,0
Exp/Cntr(USF)=0,0
Exp/Cntr=0.3,0.1

Type RM Length L Ch R = 1 ,22562   ,186.1,196.5,203.5
XS GIS Cut Line= 5
2204545.76203253654995.6753979162204625.59032154655015.828159212
2204720.77538528654999.3192191692204840.68317519654953.157219837
2204903.35411457654945.420066828
#Sta/Elev= 30
       0 2185.49    10.7 2182.68    23.1 2180.61    31.4 2178.03      52 2173.31
    64.4 2169.89      89 2165.19   101.2  2161.2   105.3 2160.47   113.4 2160.09
   121.5 2160.59   133.7 2159.71   141.8 2160.11     158 2162.17   170.2 2161.72
   225.4 2162.98     234 2162.53   255.4 2159.79   259.7    2159   269.9 2158.79
     274 2158.97  278.31 2159.77   282.3 2160.88   297.7 2162.28   306.9 2165.52
   325.3 2174.49   342.8 2186.54   355.3 2193.43   359.3  2195.5   370.6 2199.76
#Mann= 3 ,-1,0
       0      .1       0   255.4    .045       0  278.31      .1       0
#XS Ineff= 2 , 0
          182.29 2177.59
Permanent Ineff=
       F       F
Bank Sta=255.4,278.31
XS Rating Curve= 0 ,0
Exp/Cntr(USF)=0,0
Exp/Cntr=0.3,0.1

Type RM Length L Ch R = 1 ,22366   ,229.1,219.6,209
XS GIS Cut Line= 5
2204561.19071373655090.2047776432204646.41240767655118.593927224
 2204751.6376886655130.199656737 2204834.4252258 655166.56427588
 2204922.6287701655144.126532154
#Sta/Elev= 30
       0 2177.95      20 2172.31    53.7 2164.97    66.4  2160.8    70.6 2159.87
    77.5 2159.93    95.6 2160.95   103.7 2159.83   107.7 2159.82   115.7 2158.08
   119.8 2157.73   143.9 2158.65     160 2158.09   180.1 2159.17   192.2 2159.18
     205  2159.9   209.4  2159.7   222.5  2157.7   235.6 2157.17   244.3 2155.81
   246.9 2155.77   253.1  2156.1  256.84 2157.18   261.8 2158.94   270.5 2163.31
   274.9 2164.88   286.1 2165.97   312.7 2170.89   361.1 2182.29   377.1 2187.08
#Mann= 3 ,-1,0
       0      .1       0   235.6    .045       0  256.84      .1       0
#XS Ineff= 2 , 0
           144.7 2162.68
Permanent Ineff=
       F       F
Bank Sta=235.6,256.84
XS Rating Curve= 0 ,0
Exp/Cntr(USF)=0,0
Exp/Cntr=0.3,0.1