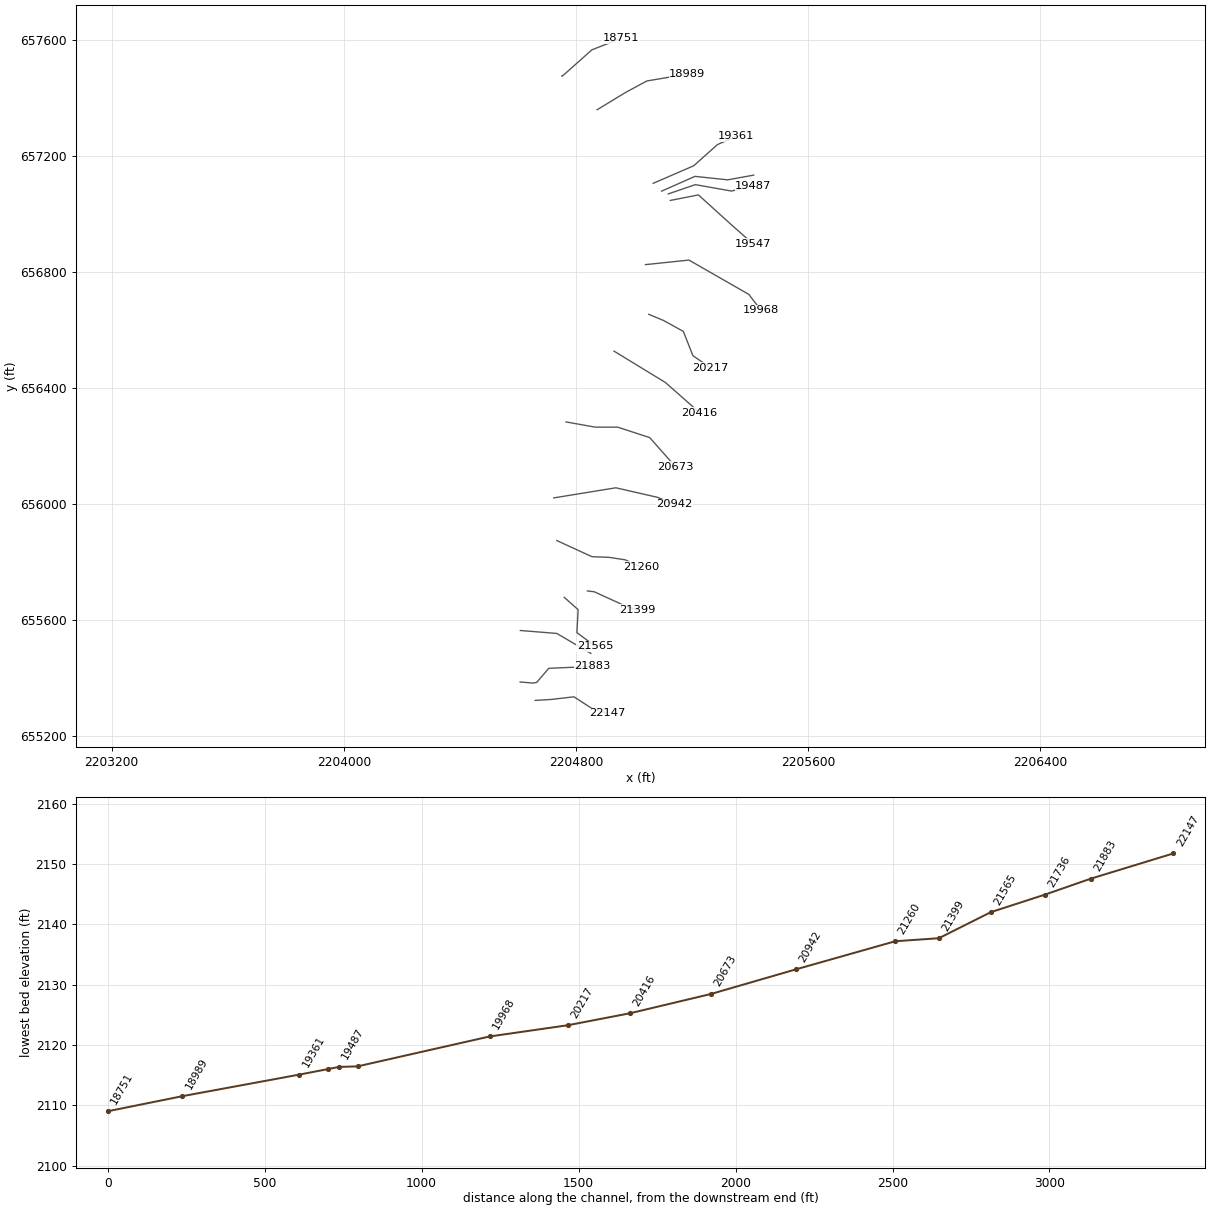
HEC-RAS study PANTHERCK.prj: PANTHERCK

--- PANTHERCK.g01 (geometry) --- (continued)

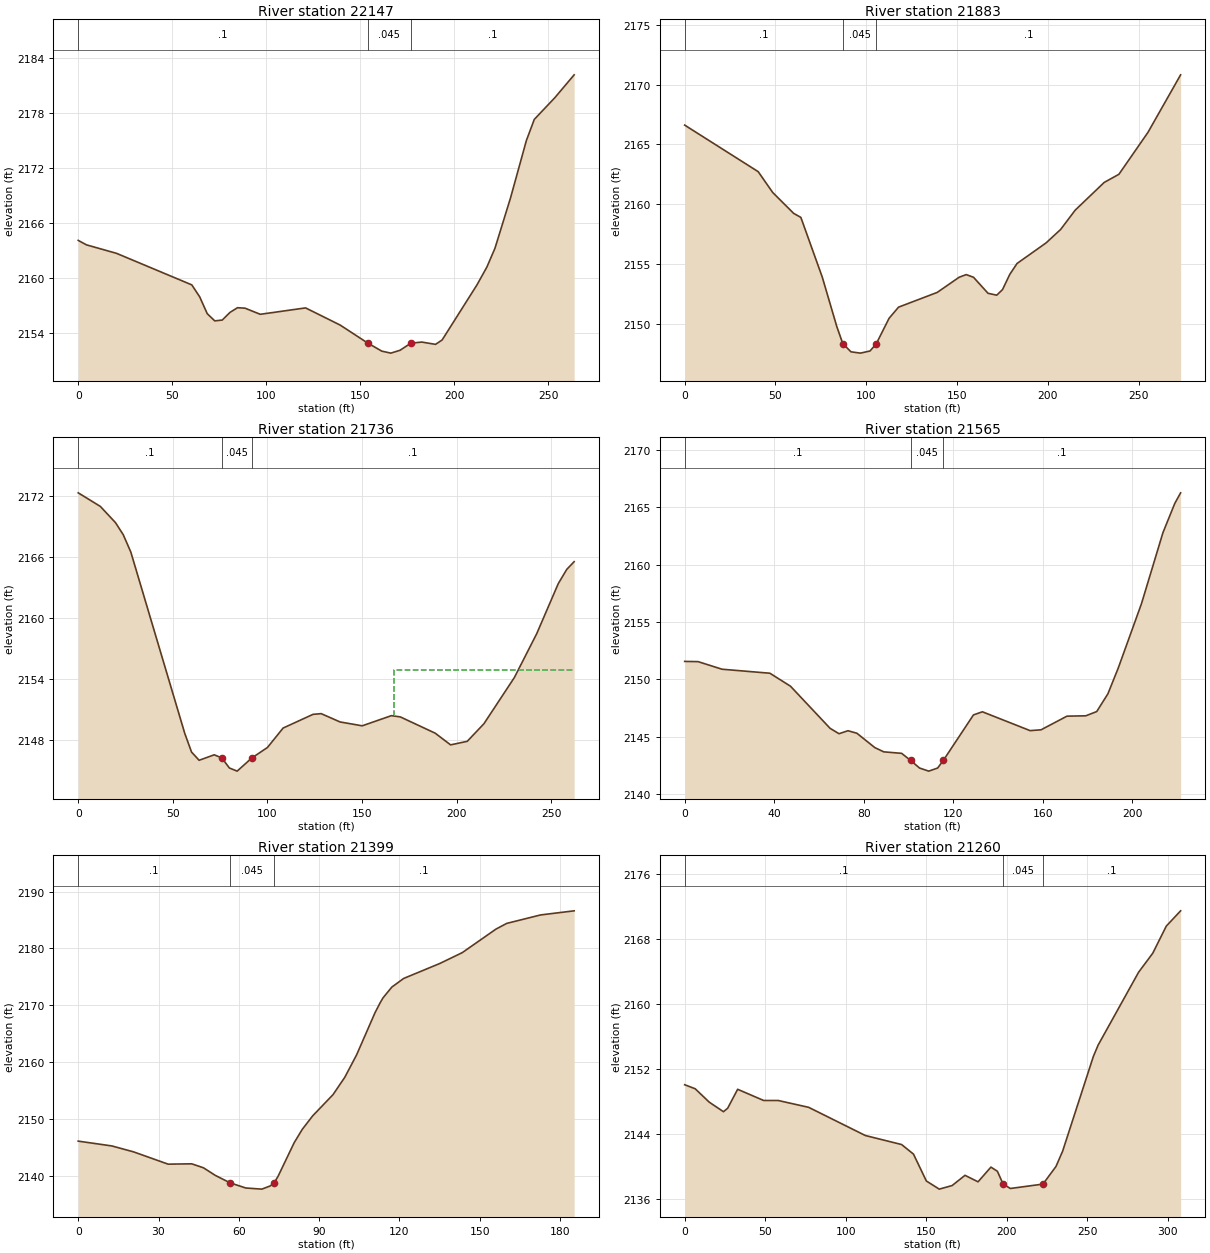
Type RM Length L Ch R = 1 ,22147   ,240.6,263.5,276.2
XS GIS Cut Line= 5
 2204659.7734472655321.1730669652204714.59798496655324.371165001
2204793.17982243655333.5085879622204855.31429856655293.303926934
2204908.31135173655276.399694457
#Sta/Elev= 30
       0 2164.09     4.4  2163.6    20.4 2162.67    60.4 2159.22    64.6 2157.91
    68.6 2156.07    72.6 2155.28    76.6 2155.37    80.7 2156.21    84.7 2156.72
    88.7 2156.67    96.8    2156   120.9  2156.7   139.3 2154.82  153.96 2152.85
   161.4 2151.97   166.2 2151.75   171.1 2152.06   176.9 2152.84   182.7 2152.96
     190 2152.71   193.5 2153.19     212 2159.21   217.3 2161.17   221.6 2163.23
   229.9 2168.76   238.3 2175.02   242.5 2177.33   253.4  2179.7   263.7 2182.21
#Mann= 3 ,-1,0
       0      .1       0  153.96    .045       0   176.9      .1       0
Bank Sta=153.96,176.9
XS Rating Curve= 0 ,0
Exp/Cntr(USF)=0,0
Exp/Cntr=0.3,0.1

Type RM Length L Ch R = 1 ,21883   ,156.4,146.9,139.1
XS GIS Cut Line= 5
2204607.87851295655384.6745390252204652.56741725655380.795315822
2204664.90293824655383.262420022 2204706.4325256655431.782135944
2204858.20418963655438.372172582
#Sta/Elev= 30
       0 2166.61    40.5 2162.72    48.5 2160.98      60 2159.24      64  2158.9
    75.8 2153.91    83.8 2149.78    87.1 2148.36    91.6 2147.67    96.8 2147.56
   102.1 2147.74   105.5 2148.33   112.6 2150.47   117.8  2151.4   139.1 2152.63
   151.2  2153.9   155.1 2154.12   159.1  2153.9   167.1 2152.56   171.9  2152.4
   175.1 2152.87   179.1 2154.14   183.1 2155.05   199.1 2156.77   207.1 2157.89
   215.1  2159.5   231.1 2161.82   239.2  2162.5   255.2    2166   273.2 2170.81
#Mann= 3 ,-1,0
       0      .1       0    87.1    .045       0   105.5      .1       0
Bank Sta=87.1,105.5
XS Rating Curve= 0 ,0
Exp/Cntr(USF)=0,0
Exp/Cntr=0.3,0.1

Type RM Length L Ch R = 1 ,21736   ,181.5,171.4,157.4
XS GIS Cut Line= 3
2204608.48903699655562.1864543992204734.10794816655552.039196247
2204851.46570536655483.149431815
#Sta/Elev= 30
       0 2172.35    11.7 2171.01    19.7 2169.41    23.8 2168.22    27.8 2166.51
    56.3 2148.63    59.9 2146.78    63.9 2145.97    71.9 2146.51    75.9  2146.2
    79.9 2145.21      84  2144.9   91.77  2146.2     100 2147.23   108.3 2149.15
   124.1  2150.5   128.4 2150.57   138.4 2149.75   150.1 2149.37   165.5 2150.37
   170.2 2150.25   188.7 2148.64   196.8 2147.49   205.6 2147.84   214.4 2149.57
   230.5 2154.13   242.3 2158.45   253.7 2163.39   258.2  2164.8   262.1 2165.56
#Mann= 3 ,-1,0
       0      .1       0    75.9    .045       0   91.77      .1       0
#XS Ineff= 2 , 0
                          166.67          2154.9
Permanent Ineff=
       F       F
Bank Sta=75.9,91.77
XS Rating Curve= 0 ,0
Exp/Cntr(USF)=0,0
Exp/Cntr=0.3,0.1

Type RM Length L Ch R = 1 ,21565   ,152.8,165.5,171.7
XS GIS Cut Line= 4
2204759.65863283655676.5730725822204807.63010337655634.084055815
 2204803.3904033655554.8509717952204866.29432108 655508.20442758
#Sta/Elev= 30
       0 2151.57       6 2151.55    16.7 2150.89    38.1 2150.54    47.3 2149.41
      65 2145.74      69 2145.27      73 2145.53      77 2145.31      85 2144.06
      89 2143.69      97 2143.56     101 2142.94     105 2142.28   109.1 2142.01
   113.1 2142.28  115.68 2142.96   129.1 2146.91   133.1 2147.18   154.4 2145.54
   159.3 2145.61   170.9  2146.8   179.3 2146.83   184.2  2147.2   189.2 2148.75
   193.8 2150.98   204.2  2156.6   213.8 2162.79   219.1 2165.34   221.7 2166.26
#Mann= 3 ,-1,0
       0      .1       0     101    .045       0  115.68      .1       0
Bank Sta=101,115.68
XS Rating Curve= 0 ,0
Exp/Cntr(USF)=0,0
Exp/Cntr=0.3,0.1

Type RM Length L Ch R = 1 ,21399   ,135.9,138.9,140.9
XS GIS Cut Line= 4
2204839.62089522655698.5996725092204863.05838511655695.721384276
2204970.37741778655646.7904843212205011.90700514655633.221411224
#Sta/Elev= 30
       0 2146.13    12.6 2145.28    20.7 2144.24    33.6 2142.08    42.4 2142.14
    46.8 2141.44    51.2 2140.11   56.72  2138.8    62.6 2137.89    68.6 2137.69
    71.7 2138.24    73.2 2138.79    74.7 2139.97    80.7 2145.86    83.7 2148.19
    87.6 2150.57    95.2  2154.3    99.6 2157.35     104 2161.28   110.9 2168.71
   112.8 2170.44   113.9 2171.33   117.2 2173.22   121.6 2174.73   135.1 2177.36
   143.5 2179.27   156.1 2183.41   160.1 2184.41   172.8  2185.9   185.3 2186.62
#Mann= 3 ,-1,0
       0      .1       0   56.72    .045       0    73.2      .1       0
Bank Sta=56.72,73.2
XS Rating Curve= 0 ,0
Exp/Cntr(USF)=0,0
Exp/Cntr=0.3,0.1

Type RM Length L Ch R = 1 ,21260   ,310.3,317.7,321
XS GIS Cut Line= 5
2204734.23727177655872.3214754042204855.43151579655816.622270846
2204913.30186121 655814.59173241 2204969.6493028655805.961944058
2205023.96620596 655781.08784822
#Sta/Elev= 30
       0 2150.04     6.5 2149.55    15.3 2147.89    24.1 2146.72    26.7 2147.15
    32.9 2149.48    49.1  2148.1    58.1  2148.1      77 2147.26   112.2 2143.79
   134.7 2142.68   142.1  2141.5   150.1 2138.19   158.1 2137.19   166.1 2137.63
   174.1 2138.89   182.2 2138.09   190.2  2139.9   194.2 2139.39   197.8  2137.8
   202.3 2137.27   222.5 2137.81   230.6 2139.98   234.7 2141.85   253.8 2153.52
   256.8 2154.93   281.9 2163.89   290.7 2166.23   299.1 2169.57     308 2171.45
#Mann= 3 ,-1,0
       0      .1       0   197.8    .045       0   222.5      .1       0
Bank Sta=197.8,222.5
XS Rating Curve= 0 ,0
Exp/Cntr(USF)=0,0
Exp/Cntr=0.3,0.1

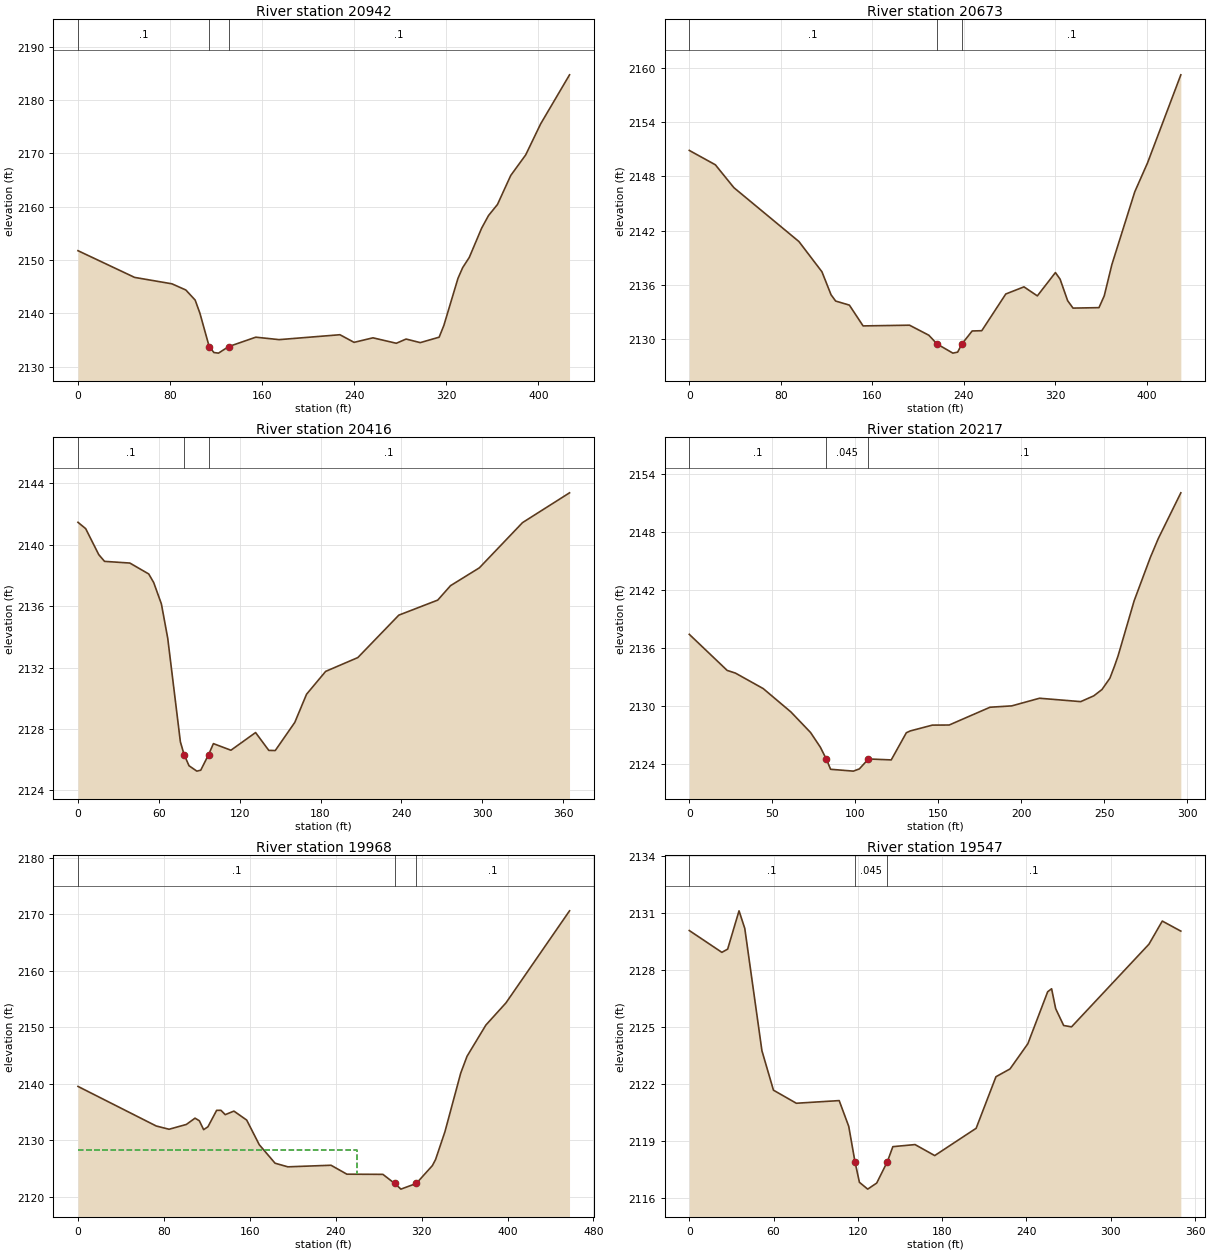
Type RM Length L Ch R = 1 ,20942   ,271.7,269.4,265.6
XS GIS Cut Line= 4
2204723.65483226656019.4401558232204937.70117741656054.311070003
2205080.98178869656021.4095963012205139.35537106 655996.99882549
#Sta/Elev= 30
       0 2151.72    49.2 2146.71    81.6 2145.51    93.7 2144.35   101.8 2142.46
   105.9 2140.02     114 2133.74   118.1 2132.62   122.1 2132.51  130.85 2133.73
   154.5  2135.5   174.8 2135.04   227.6 2135.96   239.9 2134.53   256.3 2135.38
   276.6 2134.36   285.1 2135.15   297.4 2134.48   313.8  2135.5   317.9  2137.7
   330.2 2146.55   334.3 2148.56     340 2150.46   350.7 2155.93   356.7 2158.31
   364.5 2160.39     376 2165.82     389 2169.68     402  2175.5   427.1  2184.7
#Mann= 3 ,-1,0
       0      .1       0     114    .045       0  130.85      .1       0
Bank Sta=114,130.85
XS Rating Curve= 0 ,0
Exp/Cntr(USF)=0,0
Exp/Cntr=0.3,0.1

Type RM Length L Ch R = 1 ,20673   ,258.9,257.1,256.5
XS GIS Cut Line= 5
2204765.76444387 656281.43737233 2204866.5915407656263.394628688
2204944.06920457656263.3946286882205054.44834215656227.309141402
2205143.11424218656126.996114083
#Sta/Elev= 30
       0 2150.87    22.8 2149.28      39 2146.75    95.9 2140.79     116 2137.45
     124  2134.9     128 2134.21     140 2133.76     152 2131.46   192.6 2131.54
   209.5 2130.43   216.6 2129.47   230.5 2128.45   234.7 2128.56   238.5 2129.48
   247.4  2130.9   255.8 2130.93   276.8 2134.99   292.7 2135.78   304.4 2134.78
   320.2 2137.36   324.3 2136.63   330.9 2134.25   335.6 2133.43   358.3 2133.48
   362.9 2134.78   369.6 2138.25   389.6 2146.29   400.8  2149.5   429.9 2159.23
#Mann= 3 ,-1,0
       0      .1       0   216.6    .045       0   238.5      .1       0
Bank Sta=216.6,238.5
XS Rating Curve= 0 ,0
Exp/Cntr(USF)=0,0
Exp/Cntr=0.3,0.1

Type RM Length L Ch R = 1 ,20416   ,198.3,199.7,201.7
XS GIS Cut Line= 3
2204931.33315024 656525.545080442205108.57657308656417.288618583
2205226.38507569656313.277508171
#Sta/Elev= 30
       0 2141.45     5.7 2141.04    15.4 2139.35    19.7 2138.91    38.5  2138.8
    52.5 2138.09    56.2 2137.53    61.9 2136.14    66.6 2133.91      76 2127.16
   78.73 2126.34    82.4 2125.61    88.2 2125.26    91.1 2125.32    96.9 2126.33
   100.5 2127.05   113.5 2126.62   131.8 2127.77   141.6 2126.61   146.4  2126.6
   160.9 2128.43   169.6 2130.26   183.8 2131.75   207.7 2132.65   238.1 2135.41
     267 2136.39   276.5 2137.33   297.9 2138.49   329.9 2141.43   364.8 2143.37
#Mann= 3 ,-1,0
       0      .1       0   78.73    .045       0    96.9      .1       0
Bank Sta=78.73,96.9
XS Rating Curve= 0 ,0
Exp/Cntr(USF)=0,0
Exp/Cntr=0.3,0.1

Type RM Length L Ch R = 1 ,20217   ,249.7,248.7,247.1
XS GIS Cut Line= 5
 2205051.1175734656652.5058696632205101.82593789656631.279112436
2205170.22326673656593.5426551442205203.24266686656509.814890527
2205263.38514567656468.540640363
#Sta/Elev= 30
       0 2137.41    22.8 2133.68    27.8  2133.4    44.5  2131.8    61.2 2129.38
      73 2127.26    78.9 2125.74   82.48 2124.52    85.1 2123.45    98.8 2123.26
   102.4 2123.49   107.9 2124.52   121.6 2124.42   130.7 2127.23   133.1 2127.42
   146.4 2128.02   156.5 2128.03   181.1 2129.87   194.2 2130.01   210.9  2130.8
   235.7 2130.45   243.6 2131.05   248.5  2131.7   253.3 2132.88   255.9 2134.05
   258.2 2135.18   267.9 2140.89   277.6 2145.35   282.4 2147.31     296 2152.05
#Mann= 3 ,-1,0
       0      .1       0   82.48    .045       0   107.9      .1       0
Bank Sta=82.48,107.9
XS Rating Curve= 0 ,0
Exp/Cntr(USF)=0,0
Exp/Cntr=0.3,0.1

Type RM Length L Ch R = 1 ,19968   ,418.3,420.2,407.7
XS GIS Cut Line= 4
2205039.81412624656823.840172721 2205189.4506184656839.537012546
2205395.86605458656721.219241335 2205437.9905543656666.199486603
#Sta/Elev= 30
       0 2139.55    72.8 2132.56    84.8 2131.98   100.9 2132.83     109 2133.94
     113 2133.48     117 2131.91     121 2132.42   129.1 2135.32   133.1 2135.33
   137.1 2134.56   145.2 2135.19   157.1  2133.6   168.8 2129.25   183.5 2125.98
   195.4 2125.34   235.6 2125.62   250.4 2124.04   283.9 2124.01   294.9  2122.4
   300.7  2121.4     315  2122.4     330 2125.56     333 2126.65   341.7 2131.55
   356.4 2141.91   362.3 2144.89   379.8 2150.39   398.5 2154.31   457.7 2170.58
#Mann= 3 ,-1,0
       0      .1       0   294.9    .045       0     315      .1       0
#XS Ineff= 2 , 0
           259.9 2128.27
Permanent Ineff=
       F       F
Bank Sta=294.9,315
XS Rating Curve= 0 ,0
Exp/Cntr(USF)=0,0
Exp/Cntr=0.3,0.1

Type RM Length L Ch R = 1 ,19547   ,55.4,60.3,68.5
XS GIS Cut Line= 4
2205125.40779807657045.1777185032205222.14713137657064.250514006
2205340.89770196656956.6778879522205409.20902588656896.513786152
#Sta/Elev= 30
       0 2130.09    23.2 2128.94    27.3 2129.11    35.4 2131.13    39.5  2130.2
    51.7 2123.75    59.9 2121.67    76.2 2120.98   106.7 2121.12   113.5 2119.76
  117.92  2117.9   121.1 2116.81     127 2116.45   133.4 2116.77     141  2117.9
   144.9 2118.69   160.7  2118.8   174.7 2118.22   204.2 2119.66   218.3 2122.38
   228.3 2122.79     241 2124.12   255.1 2126.86   257.9 2127.02   260.8 2125.97
   266.5 2125.08   272.1 2125.01   327.2 2129.37   336.7 2130.59   349.9 2130.06
#Mann= 3 ,-1,0
       0      .1       0  117.92    .045       0     141      .1       0
#XS Ineff= 2 , 0
            38.7 2125.51
Permanent Ineff=
       F       F
Bank Sta=117.92,141
XS Rating Curve= 0 ,0
Exp/Cntr(USF)=0,0
Exp/Cntr=0.3,0.1

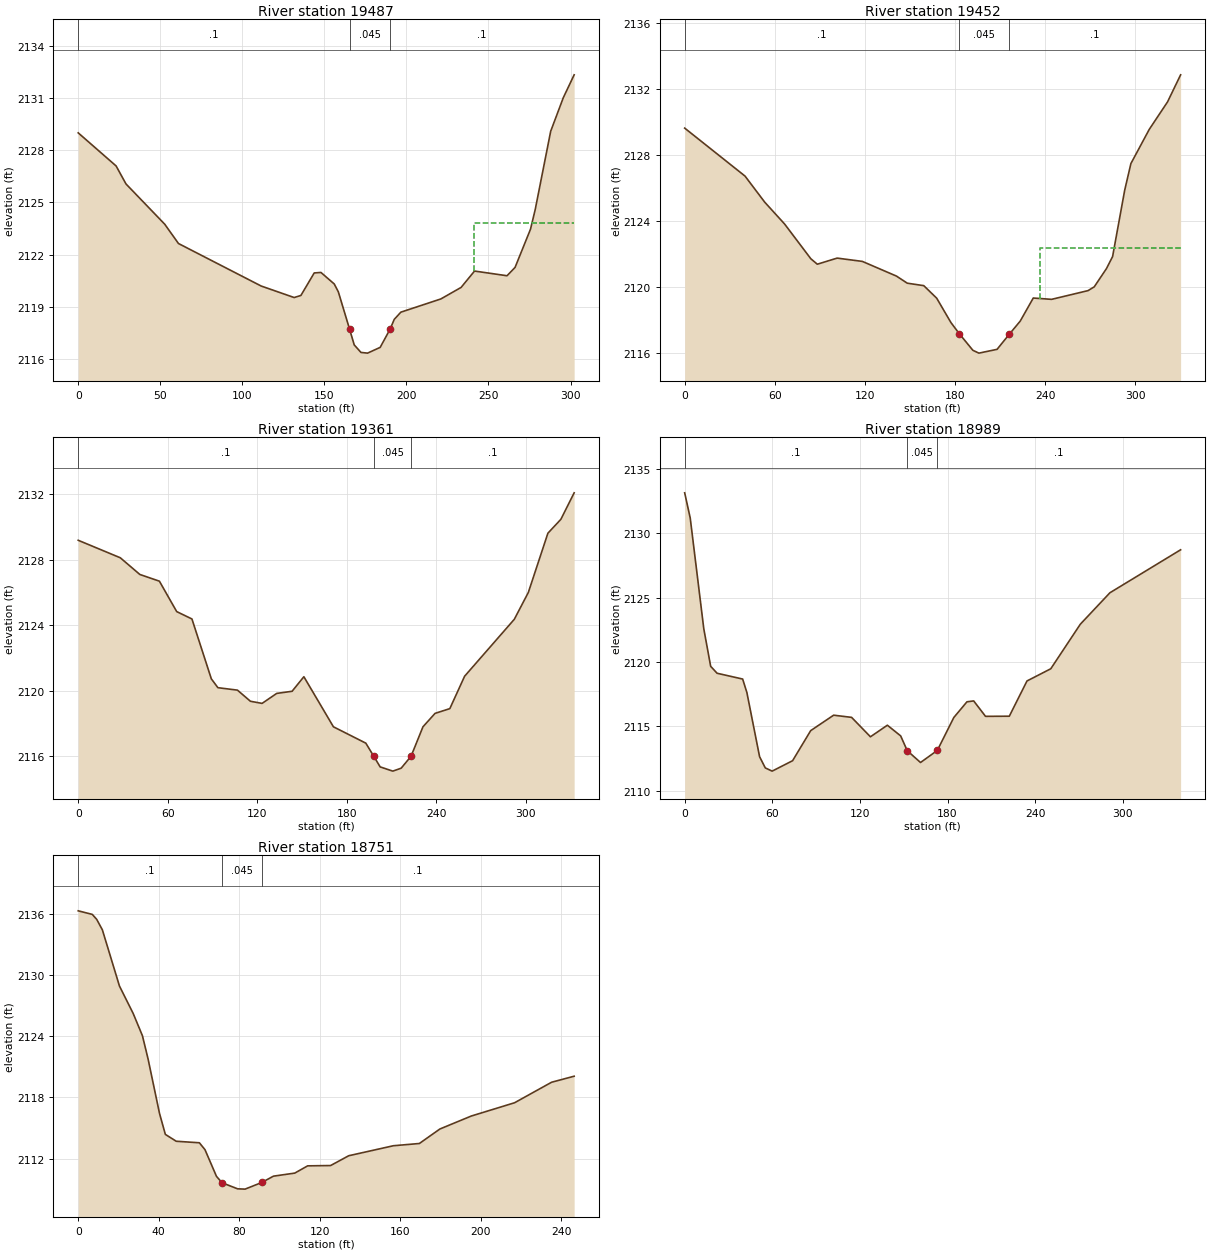
Type RM Length L Ch R = 1 ,19487   ,36.3,34.8,35.2
XS GIS Cut Line= 4
2205118.36654504 657067.726614352205211.49188819657099.674203517
2205336.15498074657077.5310284792205411.20536493  657095.3264804
#Sta/Elev= 30
       0 2128.99    23.1 2127.09    29.1 2126.06    52.7 2123.75    61.1 2122.64
   111.5  2120.2   131.6 2119.54   135.7 2119.66   143.8 2120.95   147.9 2120.98
     156 2120.32   158.5 2119.87   165.4 2117.71   168.2 2116.82   172.3 2116.39
   176.3 2116.35     184 2116.68  189.95 2117.71   192.6 2118.29   196.6  2118.7
     221 2119.46   233.3 2120.12   241.5 2121.06   261.3 2120.79   266.2 2121.27
   275.6 2123.46   278.5  2124.6   287.9 2129.08   295.6 2131.01   302.2 2132.32
#Mann= 3 ,-1,0
       0      .1       0   165.4    .045       0  189.95      .1       0
#XS Ineff= 2 , 0
                          241.44          2123.8
Permanent Ineff=
       F       F
Bank Sta=165.4,189.95
XS Rating Curve= 0 ,0
Exp/Cntr(USF)=0,0
Exp/Cntr=0.3,0.1

Type RM Length L Ch R = 1 ,19452   ,78.1,91,102.3
XS GIS Cut Line= 4
2205095.40219014657077.2786440462205210.22546497 657128.14421433
2205323.00182063657116.2167935252205412.75279553657132.464814844
#Sta/Elev= 30
       0 2129.63    40.2 2126.72    53.3 2125.14    66.5 2123.82      84 2121.71
    88.3 2121.38   101.5 2121.75   118.3 2121.55     141 2120.66   148.2 2120.23
   159.2 2120.08   167.8 2119.32   177.3 2117.84   182.9 2117.16   191.9 2116.16
   195.9 2115.99     208 2116.22     216 2117.12   223.4 2117.93   232.1 2119.33
   244.3 2119.25   268.6 2119.78   272.7 2120.01   280.8 2121.11   284.9 2121.84
     293 2125.88   297.1 2127.48   309.3 2129.55   321.5 2131.22   330.2 2132.86
#Mann= 3 ,-1,0
       0      .1       0   182.9    .045       0     216      .1       0
#XS Ineff= 2 , 0
                          236.71         2122.37
Permanent Ineff=
       F       F
Bank Sta=182.9,216
XS Rating Curve= 0 ,0
Exp/Cntr(USF)=0,0
Exp/Cntr=0.3,0.1

Type RM Length L Ch R = 1 ,19361   ,368.9,371.9,364
XS GIS Cut Line= 4
2205066.28466554657104.2063688822205206.13149897657164.804385751
2205287.86067101657237.9037694372205352.33026635657265.823672928
#Sta/Elev= 30
       0 2129.19    28.2 2128.12    41.3  2127.1    54.4 2126.69      66 2124.83
    76.2 2124.38    89.2 2120.72    93.6 2120.18   106.7 2120.03   115.4 2119.35
   123.2 2119.22     133 2119.83   143.3 2119.96   151.2 2120.85     171 2117.79
   192.7 2116.79   198.1 2115.98   202.3 2115.34   210.8 2115.08   216.4 2115.26
  223.03 2115.99     231 2117.79   239.1 2118.61     249  2118.9   258.9 2120.88
   292.2 2124.36   301.6    2126   314.7 2129.62   323.4 2130.47   332.3 2132.09
#Mann= 3 ,-1,0
       0      .1       0   198.1    .045       0  223.03      .1       0
Bank Sta=198.1,223.03
XS Rating Curve= 0 ,0
Exp/Cntr(USF)=0,0
Exp/Cntr=0.3,0.1

Type RM Length L Ch R = 1 ,18989   ,233,238,237.4
XS GIS Cut Line= 4
2204872.96915517657357.8618871772204972.00306237657417.993669325
2205044.43738548657457.1336630332205183.81701446657480.696928352
#Sta/Elev= 30
       0 2133.15     3.8 2131.19    13.1 2122.57    17.8 2119.66    22.2 2119.12
    39.7 2118.67    42.6 2117.62    51.3 2112.63    55.2 2111.76    59.9 2111.51
    73.9 2112.32    86.3 2114.66     102 2115.86   114.3 2115.69   127.2 2114.18
   138.8 2115.08   147.9 2114.25   152.4  2113.1   161.5 2112.18     173 2113.12
   184.3 2115.68   193.3  2116.9   197.9 2116.97     206 2115.77   222.3 2115.78
   234.4 2118.52   250.7 2119.47   270.9 2122.93   291.2 2125.38   339.6 2128.72
#Mann= 3 ,-1,0
       0      .1       0   152.4    .045       0     173      .1       0
Bank Sta=152.4,173
XS Rating Curve= 0 ,0
Exp/Cntr(USF)=0,0
Exp/Cntr=0.3,0.1

Type RM Length L Ch R = 1 ,18751   ,174.6,203,232.7
XS GIS Cut Line= 4
2204751.38753278657474.4298344142204753.28021363657473.866618029
 2204855.0824376657564.4750231432204955.69479514 657604.15867892
#Sta/Elev= 30
       0 2136.27       7 2135.92     9.2 2135.43      12 2134.41    20.5  2128.9
    27.3 2126.22    31.9 2124.04    34.7 2121.77    40.4 2116.42    43.3 2114.37
    48.7  2113.7    60.2 2113.55      63 2112.87    68.7 2110.26    71.5 2109.63
    79.2 2109.04    82.9 2109.01    91.2 2109.66      97 2110.28   107.6 2110.58
     114 2111.29   125.4 2111.32   134.4 2112.28   156.6 2113.26   169.5 2113.48
   179.7  2114.9   195.3 2116.17   216.8 2117.47   235.2 2119.48   246.4 2120.07
#Mann= 3 ,-1,0
       0      .1       0    71.5    .045       0    91.2      .1       0
Bank Sta=71.5,91.2
XS Rating Curve= 0 ,0
Exp/Cntr(USF)=0,0
Exp/Cntr=0.3,0.1