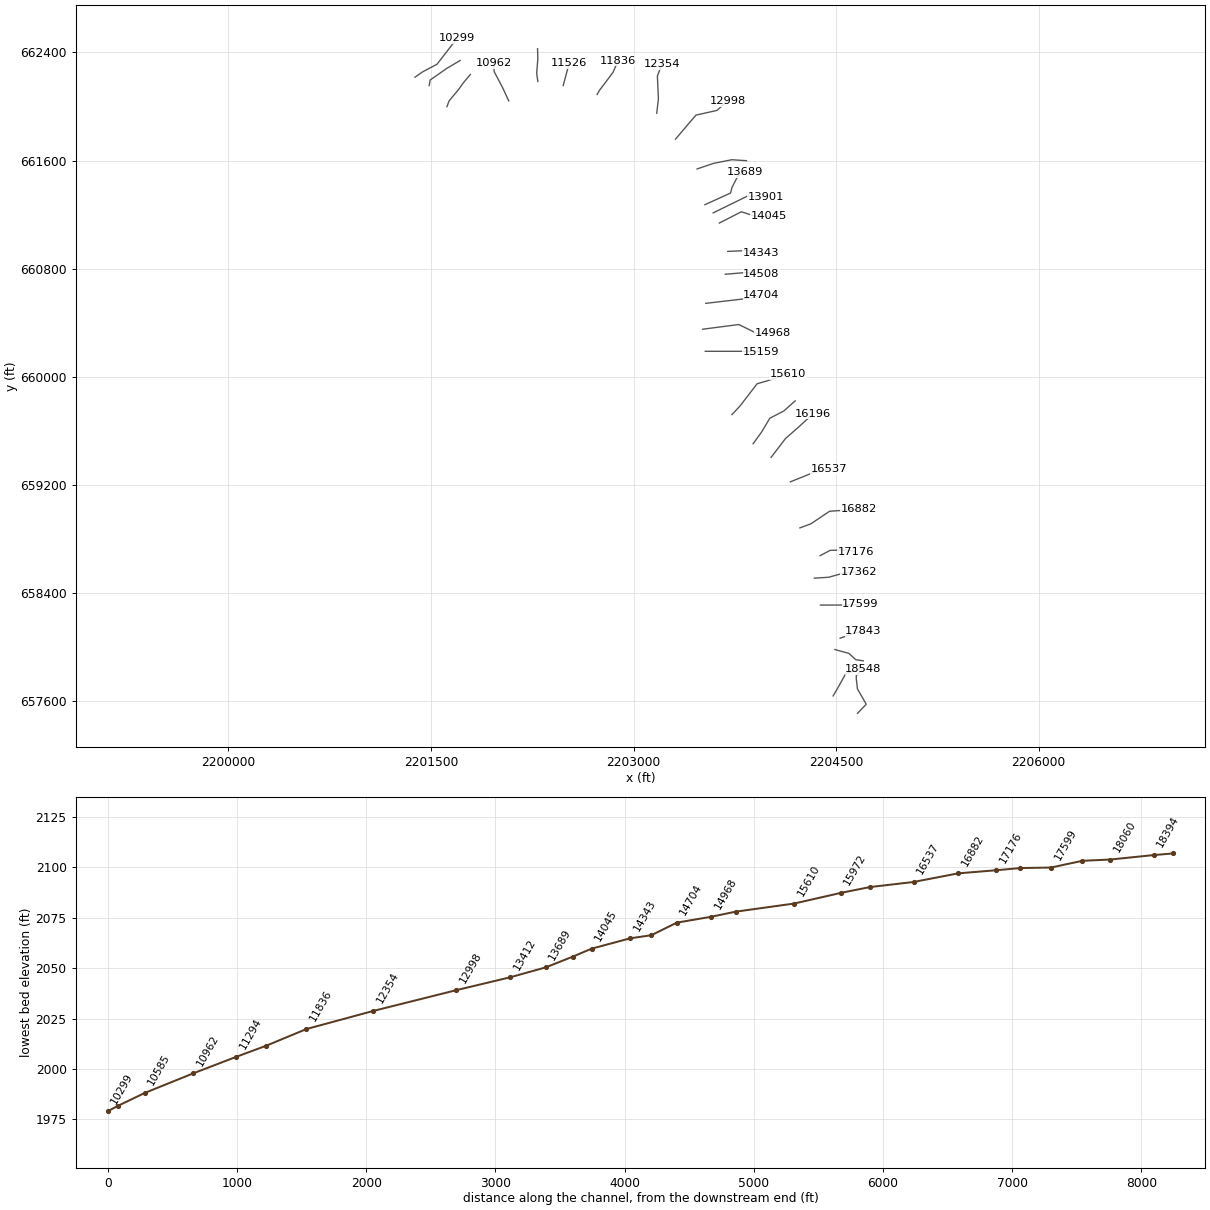
HEC-RAS study PANTHERCK.prj: PANTHERCK

--- PANTHERCK.g01 (geometry) --- (continued)

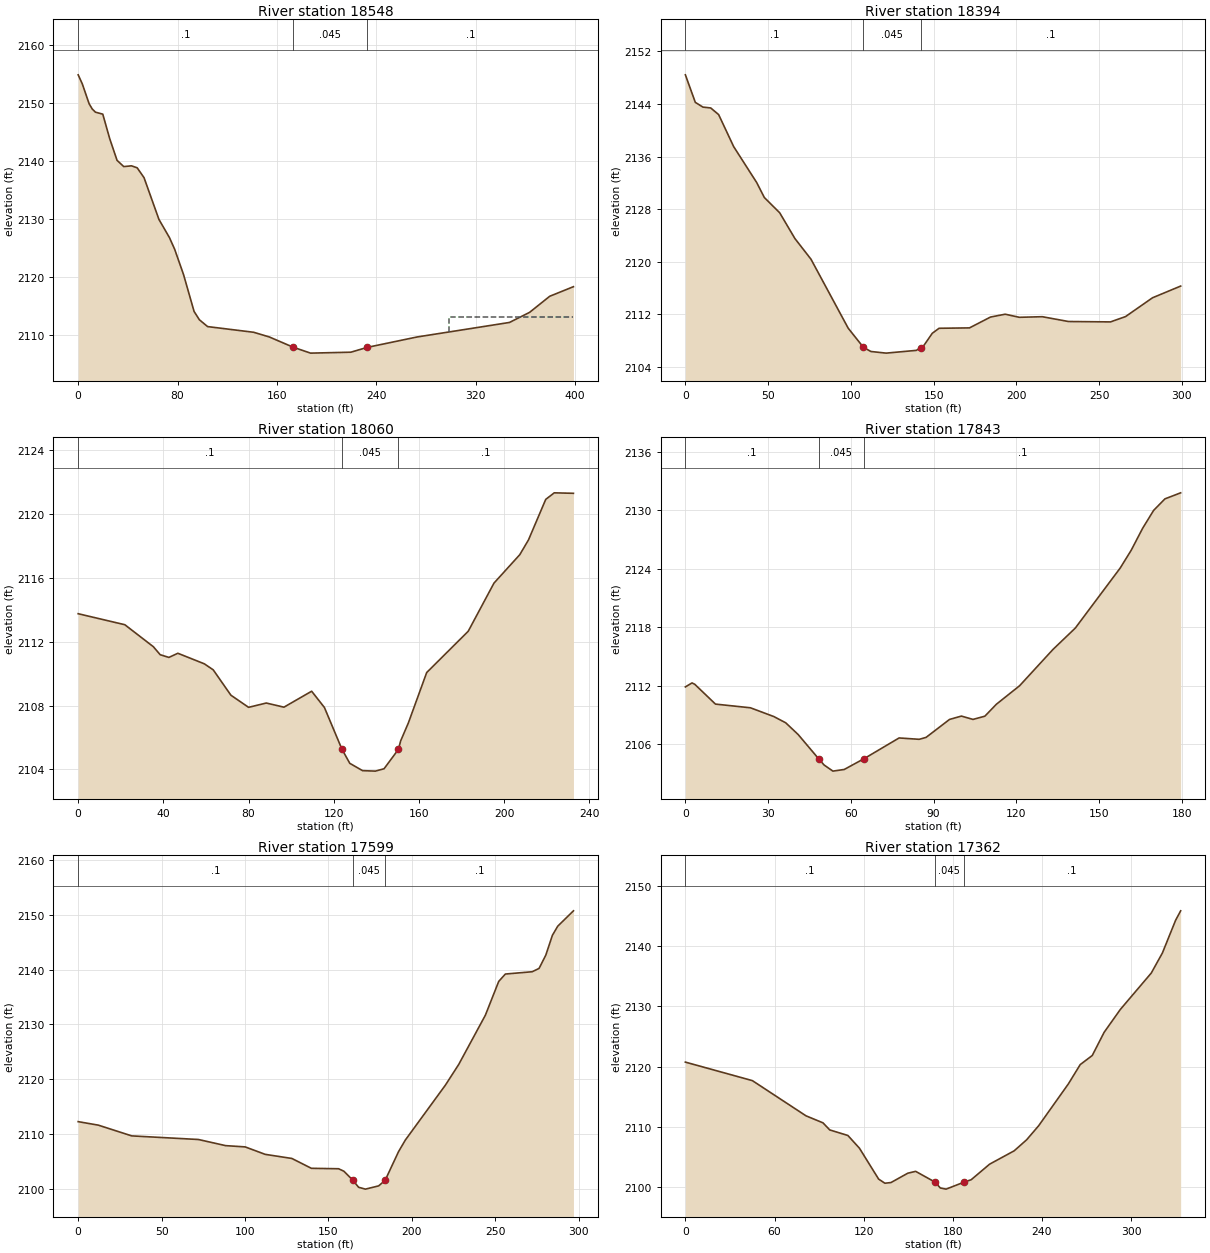
Type RM Length L Ch R = 1 ,18548   ,177.3,153.9,127.7
XS GIS Cut Line= 6
2204658.61784433 657506.782118682204723.03429358657574.443691303
2204658.02434752657688.4335372582204649.72761728657761.218488883
2204649.57865301657787.5831731932204702.35762926657835.437680037
#Sta/Elev= 30
       0 2154.84     3.3 2153.29     8.8 2149.87    11.3 2148.96    13.9 2148.41
    19.8 2148.07    25.4 2143.84    31.3 2140.11    36.7 2139.04    42.9 2139.17
    47.5 2138.83      53 2137.14      65 2129.95    73.5  2126.8    77.7 2124.79
    84.8 2120.46    93.3  2114.1    97.6 2112.66   104.2 2111.49   141.3 2110.51
   153.8 2109.71   173.2 2107.93   187.1 2106.92   219.5 2107.08  232.71 2107.91
   272.8  2109.7   347.2  2112.2   363.4 2113.94   379.6 2116.71   398.7 2118.36
#Mann= 3 ,-1,0
       0      .1       0   173.2    .045       0  232.71      .1       0
#XS Ineff= 2 , 0
                          298.45         2113.08
Permanent Ineff=
       F       F
Bank Sta=173.2,232.71
XS Rating Curve= 0 ,0
Exp/Cntr(USF)=0,0
Exp/Cntr=0.3,0.1

Type RM Length L Ch R = 1 ,18394   ,360.2,333.9,300.3
XS GIS Cut Line= 4
2204477.90517859657635.9862180572204516.50273586657702.039452811
2204570.30466697657798.6961311182204676.26316037657835.545819916
#Sta/Elev= 30
       0 2148.43       6 2144.24    10.6 2143.52    15.3 2143.39    20.1 2142.38
    29.2  2137.5    43.1 2132.04    47.7 2129.77      57 2127.44    66.2 2123.52
    75.9 2120.38    98.4 2109.88   107.6 2106.97   112.1 2106.34   121.3 2106.09
   139.6 2106.51  142.12 2106.93   144.2 2107.28   149.2 2109.11   153.3 2109.87
   171.7 2109.93   184.4 2111.58   193.3 2112.01   201.8 2111.54   215.7 2111.63
   231.5  2110.9   256.9 2110.84     266 2111.65   282.3 2114.51   299.3 2116.29
#Mann= 3 ,-1,0
       0      .1       0   107.6    .045       0  142.12      .1       0
Bank Sta=107.6,142.12
XS Rating Curve= 0 ,0
Exp/Cntr(USF)=0,0
Exp/Cntr=0.3,0.1

Type RM Length L Ch R = 1 ,18060   ,203.8,216.9,228.3
XS GIS Cut Line= 4
2204491.06607586 657979.422965832204594.14668276657951.015576545
2204645.86329611 657904.217838582204701.00821656657895.759647783
#Sta/Elev= 30
       0 2113.76    21.9 2113.07    35.3 2111.69    38.5 2111.19    42.6 2111.02
    46.8 2111.28    59.2 2110.62    63.4 2110.24    71.7 2108.65      80 2107.89
    88.3 2108.16    96.6  2107.9   109.6  2108.9   115.6 2107.88   123.8 2105.27
   127.5 2104.38   133.5 2103.92   139.5 2103.89   143.6 2104.04  150.31 2105.25
   151.4 2105.79     155 2106.91   163.6 2110.07   183.1 2112.66   195.2 2115.68
   207.3 2117.46   211.4 2118.39   219.5 2120.93   223.5 2121.34   232.5 2121.31
#Mann= 3 ,-1,0
       0      .1       0   123.8    .045       0  150.31      .1       0
Bank Sta=123.8,150.31
XS Rating Curve= 0 ,0
Exp/Cntr(USF)=0,0
Exp/Cntr=0.3,0.1

Type RM Length L Ch R = 1 ,17843   ,245.8,243.9,239.9
XS GIS Cut Line= 3
2204529.90330797658063.138676008 2204640.8025011658102.684124722
2204701.84004151658113.000328734
#Sta/Elev= 30
       0 2111.88     2.4 2112.29     3.4 2112.15    10.9 2110.12    23.6 2109.74
    32.1 2108.84    36.4  2108.2    40.9    2107   48.34 2104.51    50.3 2103.88
    53.5 2103.25    57.6 2103.42   64.83 2104.53    77.5 2106.65    84.8 2106.51
    87.3 2106.71    95.8 2108.55   100.1 2108.89   104.3 2108.55   108.6 2108.88
   112.8 2110.11   121.2    2112   133.3 2115.72   141.4 2117.91   157.7 2124.07
   161.7  2125.9   165.8 2128.13   169.8 2129.97   173.9 2131.15   179.6 2131.77
#Mann= 3 ,-1,0
       0      .1       0   48.34    .045       0   64.83      .1       0
Bank Sta=48.34,64.83
XS Rating Curve= 0 ,0
Exp/Cntr(USF)=0,0
Exp/Cntr=0.3,0.1

Type RM Length L Ch R = 1 ,17599   ,234.5,236.8,238.9
XS GIS Cut Line= 3
2204384.11723093658308.5344051632204635.05640406658309.312293511
2204680.61963846658315.330079185
#Sta/Elev= 30
       0 2112.23    12.1 2111.59    32.1 2109.63    72.1 2108.97    88.4 2107.85
   100.1 2107.62   112.1 2106.26   128.1 2105.51   139.8 2103.71   156.1 2103.63
  159.29 2103.18  164.66 2101.54   168.1 2100.25   172.2 2099.91   180.1  2100.5
   184.1 2101.53   184.1 2101.57     192 2106.72   196.1 2108.86   220.1 2118.88
   228.1 2122.66   244.1 2131.66   252.1 2137.83   256.1 2139.18   272.2  2139.6
   276.3 2140.21   280.3 2142.61   284.3 2146.26   287.5 2147.92   296.9 2150.72
#Mann= 3 ,-1,0
       0      .1       0  164.66    .045       0   184.1      .1       0
Bank Sta=164.66,184.1
XS Rating Curve= 0 ,0
Exp/Cntr(USF)=0,0
Exp/Cntr=0.3,0.1

Type RM Length L Ch R = 1 ,17362   ,187.6,186.2,182.9
XS GIS Cut Line= 4
2204339.14083623658507.8539222242204444.73671249658514.649596246
2204565.43629944658547.9193541862204667.56671916658554.882791894
#Sta/Elev= 30
       0 2120.73    45.1 2117.66    81.2 2111.82    92.6 2110.66    97.2 2109.48
   109.4 2108.56   117.2 2106.44   130.1 2101.32   134.3 2100.64   138.4 2100.75
   149.7  2102.3     155 2102.61   168.12100.821   171.6 2099.85   175.5 2099.66
   187.3 2100.79   192.4 2101.22   204.8  2103.8   221.3 2106.01   229.7 2107.84
   237.8 2110.17   257.8 2117.11   265.8 2120.32   273.9 2121.83   281.9 2125.68
   292.8 2129.47   313.6  2135.5   321.1 2138.83     330 2144.26   333.4 2145.83
#Mann= 3 ,-1,0
       0      .1       0   168.1    .045       0   187.3      .1       0
Bank Sta=168.1,187.3
XS Rating Curve= 0 ,0
Exp/Cntr(USF)=0,0
Exp/Cntr=0.3,0.1

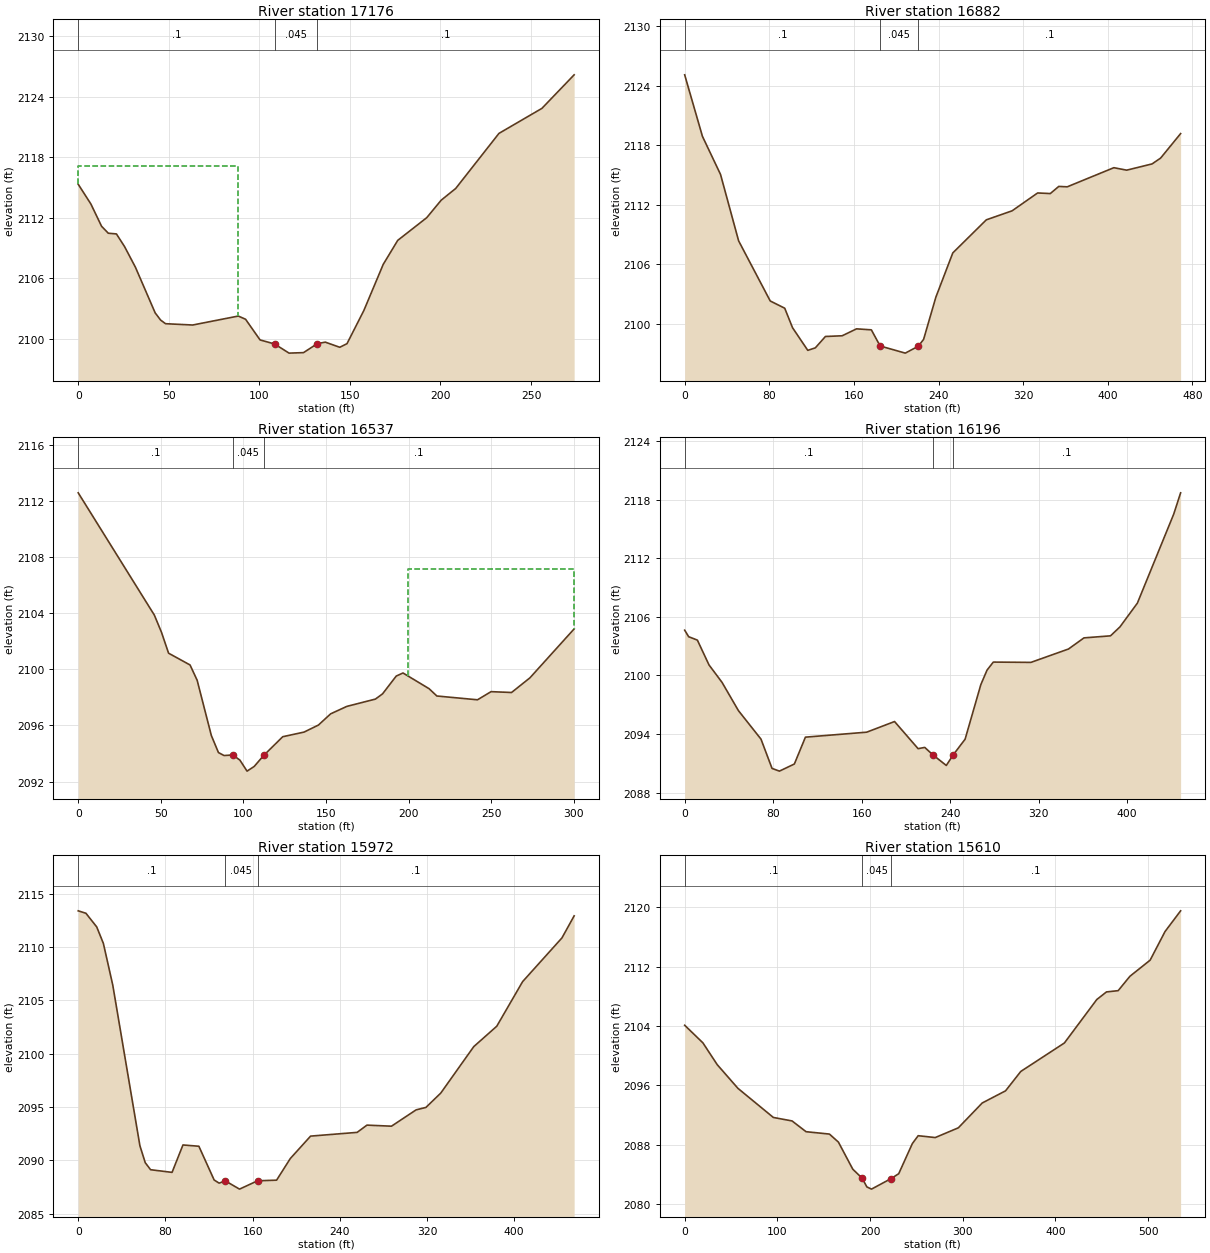
Type RM Length L Ch R = 1 ,17176   ,281.5,294.5,299.1
XS GIS Cut Line= 4
2204381.48993853658674.4684922162204455.99585639658713.631859299
2204580.17238617  658717.45267562204644.17105921658704.079818547
#Sta/Elev= 30
       0 2115.33       7 2113.37    12.9 2111.16    16.6 2110.47    21.1  2110.4
    25.6 2109.14    31.6 2107.09    42.5 2102.56    45.5 2101.85    48.2 2101.49
    63.2 2101.36    88.4 2102.25    92.4 2101.93   100.4 2099.88   108.4 2099.48
   116.4 2098.57   124.4 2098.62     132 2099.51   136.4 2099.66   144.4 2099.15
   148.4 2099.51   157.7  2102.8   168.4 2107.38   176.4 2109.76   192.4 2112.01
   200.4 2113.75   208.4 2114.91   232.3 2120.38     256 2122.86   273.8 2126.19
#Mann= 3 ,-1,0
       0      .1       0   108.4    .045       0     132      .1       0
#XS Ineff= 2 , 0
           88.06 2117.16
Permanent Ineff=
       F       F
Bank Sta=108.4,132
XS Rating Curve= 0 ,0
Exp/Cntr(USF)=0,0
Exp/Cntr=0.3,0.1

Type RM Length L Ch R = 1 ,16882   ,347.5,345.3,341.8
XS GIS Cut Line= 4
2204232.43389968658880.079639983 2204313.5582298658910.531451148
 2204451.8668675659003.2486506252204667.09417817659018.361748965
#Sta/Elev= 30
       0 2125.11    16.8  2118.9    33.9 2115.06      51 2108.36    80.9 2102.29
    94.6 2101.56     102 2099.59   116.4 2097.31   123.5 2097.56   133.1 2098.71
   148.9 2098.78   162.5 2099.48   176.5 2099.38   184.8 2097.75   208.6 2097.03
   220.9 2097.73   225.9 2098.42   237.5 2102.68   253.5 2107.14   285.2 2110.48
   309.6 2111.39   333.7 2113.19   345.7 2113.13   353.7 2113.85   361.7 2113.81
   405.8 2115.74   417.9 2115.49   441.9 2116.12     450 2116.71   468.9 2119.18
#Mann= 3 ,-1,0
       0      .1       0   184.8    .045       0   220.9      .1       0
Bank Sta=184.8,220.9
XS Rating Curve= 0 ,0
Exp/Cntr(USF)=0,0
Exp/Cntr=0.3,0.1

Type RM Length L Ch R = 1 ,16537   ,336.3,340.8,342.5
XS GIS Cut Line= 3
2204161.45166973 659220.896193662204333.38840327659290.530570743
2204445.14728007659316.321080774
#Sta/Elev= 30
       0 2112.57    46.1 2103.86    50.4 2102.64    54.7 2101.15    67.7 2100.31
      72 2099.22    80.6 2095.28    84.9 2094.07    88.3 2093.86    93.6  2093.9
    97.9 2093.53   102.2 2092.75   106.5 2093.08  112.39 2093.88   123.8  2095.2
   136.7 2095.53   145.4 2096.03   152.8 2096.83   162.6 2097.36   179.9 2097.88
   184.2 2098.25   192.5 2099.52   196.6 2099.74   212.4 2098.62   217.1  2098.1
   241.7 2097.83   249.9 2098.41   262.3 2098.35   273.4 2099.39   300.2 2102.88
#Mann= 3 ,-1,0
       0      .1       0    93.6    .045       0  112.39      .1       0
#XS Ineff= 2 , 0
                          199.35         2107.15
Permanent Ineff=
       F       F
Bank Sta=93.6,112.39
XS Rating Curve= 0 ,0
Exp/Cntr(USF)=0,0
Exp/Cntr=0.3,0.1

Type RM Length L Ch R = 1 ,16196   ,219.9,224.1,221.8
XS GIS Cut Line= 4
2204018.83580794 659402.346717842204124.96959407659541.381977677
2204218.36732587659623.1049930012204328.74646345659723.932089829
#Sta/Elev= 30
       0 2104.64     3.6 2103.97    11.5 2103.62      22 2101.08    33.8 2099.29
    48.6  2096.4      69 2093.48      79 2090.48    85.7  2090.2    99.2 2090.93
   109.2 2093.68   164.6 2094.19   189.8 2095.28   211.1  2092.5   217.1 2092.63
  224.23 2091.89   236.6 2090.78     243 2091.89   253.6 2093.47   267.8 2099.05
   273.4 2100.54   279.1 2101.37   313.1 2101.34   347.1 2102.71   361.1 2103.85
   385.1 2104.06   393.6 2104.97   409.4 2107.41   442.3 2116.54   448.5 2118.71
#Mann= 3 ,-1,0
       0      .1       0  224.23    .045       0     243      .1       0
Bank Sta=224.23,243
XS Rating Curve= 0 ,0
Exp/Cntr(USF)=0,0
Exp/Cntr=0.3,0.1

Type RM Length L Ch R = 1 ,15972   ,353.8,361.8,350.3
XS GIS Cut Line= 5
2203885.69686955659503.4096675272203948.19787695659589.495960725
2204009.51962005659692.0919539892204112.11561331659745.158847056
2204197.02264222659820.631761641
#Sta/Elev= 30
       0  2113.4     7.1 2113.17      17 2111.89    23.1 2110.34    31.7 2106.44
    56.6 2091.38    61.5 2089.79    66.4 2089.13    86.1 2088.88    96.1 2091.45
   110.7 2091.33   124.7 2088.17   129.3 2087.87  134.86 2088.09     148 2087.31
   164.5 2088.09     182 2088.15   194.6 2090.18   213.2 2092.28   255.9 2092.63
   264.9 2093.31   287.4 2093.21     310 2094.74     319 2094.97   332.6 2096.31
   362.9 2100.67     384 2102.58   407.7 2106.76   443.8 2110.86     455 2112.93
#Mann= 3 ,-1,0
       0      .1       0  134.86    .045       0   164.5      .1       0
Bank Sta=134.86,164.5
XS Rating Curve= 0 ,0
Exp/Cntr(USF)=0,0
Exp/Cntr=0.3,0.1

Type RM Length L Ch R = 1 ,15610   ,454.9,450.9,425.4
XS GIS Cut Line= 5
 2203729.0530992659718.730917007 2203790.3748423659784.769717269
2203915.37685708659947.508189342 2203986.1327145659967.555682279
2204144.15412942660019.443311056
#Sta/Elev= 30
       0 2104.12    19.7 2101.74    35.1 2098.81    57.5 2095.61    95.7 2091.69
   115.9 2091.22     131 2089.77   156.2 2089.45   165.9 2088.37   181.4 2084.72
   191.6 2083.49   196.6 2082.33   201.6 2082.03   222.9 2083.46     231 2084.11
   245.7 2088.17     252 2089.23   270.4 2088.98   295.3 2090.29   321.1 2093.64
   346.3 2095.28   362.7 2097.89   409.8 2101.73   444.7 2107.58   455.2 2108.61
   467.8 2108.78   480.5 2110.72   502.3 2112.89   518.4 2116.75   535.2 2119.54
#Mann= 3 ,-1,0
       0      .1       0   191.6    .045       0   222.9      .1       0
Bank Sta=191.6,222.9
XS Rating Curve= 0 ,0
Exp/Cntr(USF)=0,0
Exp/Cntr=0.3,0.1

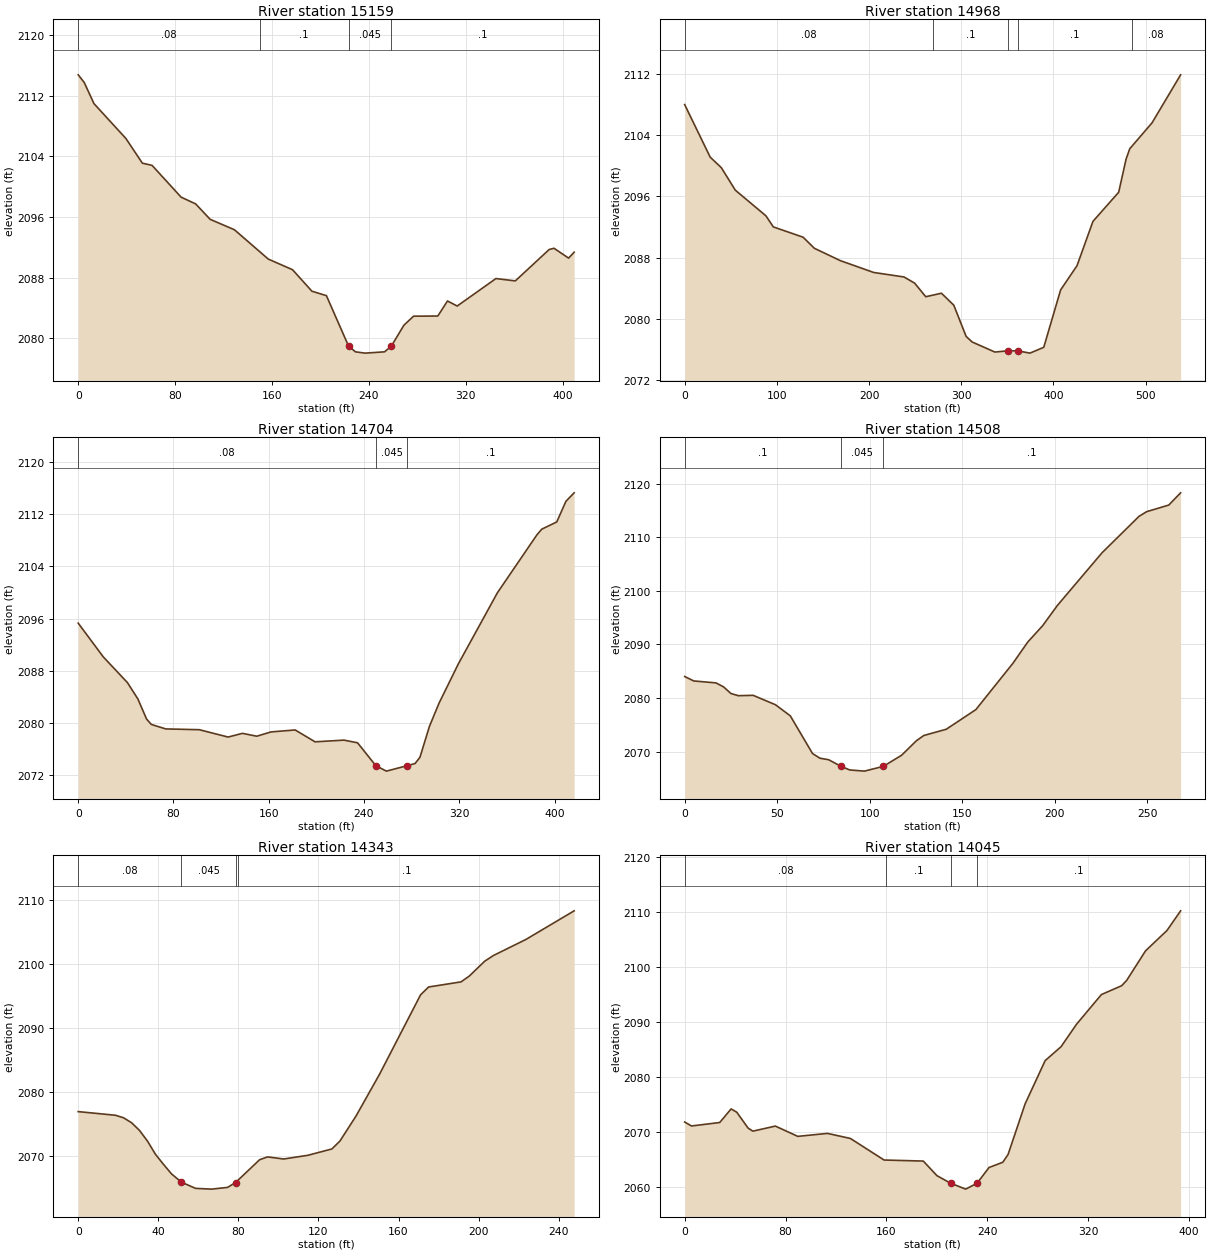
Type RM Length L Ch R = 1 ,15159   ,198.5,191.3,181.7
XS GIS Cut Line= 3
2203531.19687223660187.5632760092203839.54929194660187.563276009
2203940.80092392660185.652867859
#Sta/Elev= 30
       0 2114.78       5 2113.76      13 2110.98    39.4 2106.37      53 2103.11
      61 2102.82      85 2098.62      97 2097.73     109 2095.69     129 2094.32
     157 2090.44     177 2089.04     193  2086.2     205 2085.61  223.29 2078.95
     229 2078.19     237 2078.02     253 2078.19   258.6 2078.94     269 2081.71
     277  2082.9     297 2082.92     305 2084.91     313 2084.24     345 2087.87
     361 2087.56     389 2091.71     393 2091.87     405 2090.57   409.6 2091.35
#Mann= 4 ,-1,0
       0     .08       0     150      .1       0  223.29    .045       0
   258.6      .1       0
Bank Sta=223.29,258.6
XS Rating Curve= 0 ,0
Exp/Cntr(USF)=0,0
Exp/Cntr=0.3,0.1

Type RM Length L Ch R = 1 ,14968   ,260,264,260.9
XS GIS Cut Line= 4
2203512.73901615660351.1530292232203779.85362387660385.779056408
2203928.44092446660312.6646704032204031.03691772660323.278049017
#Sta/Elev= 30
       0 2108.04    27.7 2101.15    39.8 2099.77    54.9 2096.83    88.2 2093.46
    96.2 2092.01   128.5 2090.66   140.7 2089.21   169.1 2087.58   205.1 2086.04
     238 2085.45   249.5 2084.64   261.6 2082.86   278.6 2083.32     292 2081.75
   305.4 2077.66   311.9 2076.93   336.6 2075.61  350.43 2075.77   361.3 2075.77
   374.6 2075.47   389.6 2076.23   407.9 2083.75   425.7 2086.93     443 2092.74
   470.9 2096.55   478.9 2100.88   482.9 2102.25   507.1 2105.65   538.1 2111.94
#Mann= 5 ,-1,0
       0     .08       0  269.35      .1       0  350.43    .045       0
   361.3      .1       0  484.95     .08       0
Bank Sta=350.43,361.3
XS Rating Curve= 0 ,0
Exp/Cntr(USF)=0,0
Exp/Cntr=0.3,0.1

Type RM Length L Ch R = 1 ,14704   ,196.1,196.2,195
XS GIS Cut Line= 3
2203535.17173988 660542.550816172203877.73255997660582.716192902
2203946.12988881660603.942950129
#Sta/Elev= 30
       0  2095.3    21.1 2090.11    41.3 2086.18    50.1 2083.67    57.4 2080.58
    61.4 2079.75    73.5 2079.06   101.7 2078.94   125.9 2077.81   137.9 2078.38
     150 2077.94   161.9  2078.6   182.2  2078.9   198.9 2077.08   223.2 2077.34
   234.6 2076.93  249.92 2073.42   258.8 2072.58   276.4 2073.42   282.9 2073.75
     287 2074.71     295 2079.47   303.1 2083.04   319.2 2089.03     352 2099.95
   385.2 2108.85   389.3 2109.73   401.9 2110.84   409.6 2114.01   416.5 2115.31
#Mann= 3 ,-1,0
       0     .08       0  249.92    .045       0   276.4      .1       0
Bank Sta=249.92,276.4
XS Rating Curve= 0 ,0
Exp/Cntr(USF)=0,0
Exp/Cntr=0.3,0.1

Type RM Length L Ch R = 1 ,14508   ,165.3,164.9,164.3
XS GIS Cut Line= 3
2203679.29369637660758.0919903712203836.52893509660771.194926931
2203946.59360219660763.333164995
#Sta/Elev= 30
       0 2084.01     4.9 2083.18    16.9 2082.82      21 2082.08      25 2080.84
      29 2080.43      37  2080.5    49.1 2078.74    57.1 2076.67    69.1 2069.65
    73.1 2068.77    77.8 2068.49   84.62 2067.24    89.2 2066.58    97.2 2066.36
   107.4 2067.25   117.3 2069.33   125.3 2072.04   129.3 2073.01   141.4 2074.17
   157.4 2077.83   177.5  2086.5   185.5 2090.45   193.5 2093.48   201.5 2097.27
   225.6 2107.08   245.6 2113.88   249.7 2114.75   261.7 2115.99   268.1 2118.27
#Mann= 3 ,-1,0
       0      .1       0   84.62    .045       0   107.4      .1       0
Bank Sta=84.62,107.4
XS Rating Curve= 0 ,0
Exp/Cntr(USF)=0,0
Exp/Cntr=0.3,0.1

Type RM Length L Ch R = 1 ,14343   ,302.2,298,292.8
XS GIS Cut Line= 3
2203697.63780756660927.1198719932203843.08040337660933.671340273
2203943.97301488660917.947816401
#Sta/Elev= 30
       0  2076.9    18.6 2076.33    22.6 2075.94    26.6 2075.18    30.6 2073.97
    34.6  2072.3    38.6 2070.23    42.4 2068.74    46.6 2067.18   51.53 2065.89
    58.6 2064.92    66.6  2064.8    74.6 2065.07    78.6 2065.83    90.6 2069.39
    94.6 2069.83   102.6  2069.5   114.7 2070.08   126.7 2071.07   130.7  2072.3
   138.7 2076.18   150.5 2082.73     171 2095.13     175 2096.35   191.2 2097.15
   195.3 2098.05     203 2100.37   207.4 2101.27   223.6 2103.77   247.7 2108.24
#Mann= 4 ,-1,0
       0     .08       0   51.53    .045       0    78.6     .08       0
      80      .1       0
Bank Sta=51.53,78.6
XS Rating Curve= 0 ,0
Exp/Cntr(USF)=0,0
Exp/Cntr=0.3,0.1

Type RM Length L Ch R = 1 ,14045   ,140,143.3,145.8
XS GIS Cut Line= 4
2203635.40440837661137.1928488152203798.53041907661220.625650934
2203908.59508617661185.247722223 2204002.9362294661186.558015879
#Sta/Elev= 30
       0 2071.88     5.4 2071.16    27.8 2071.79    36.8 2074.26    41.3 2073.66
    50.3 2070.77    54.1 2070.22    71.9 2071.14    89.7 2069.27   113.2 2069.81
   131.4 2068.89   158.1 2064.97   189.2 2064.78     200 2062.13   210.8 2060.76
   222.8 2059.68   231.8 2060.74   241.3 2063.61   252.2 2064.56   256.4 2065.98
   269.9 2075.17   285.8 2083.04   298.4 2085.57   310.6 2089.63   330.4 2095.05
   346.4 2096.65   350.4 2097.61   365.4    2103   382.4  2106.7   393.2 2110.27
#Mann= 4 ,-1,0
       0     .08       0     160      .1       0   210.8    .045       0
   231.8      .1       0
Bank Sta=210.8,231.8
XS Rating Curve= 0 ,0
Exp/Cntr(USF)=0,0
Exp/Cntr=0.3,0.1

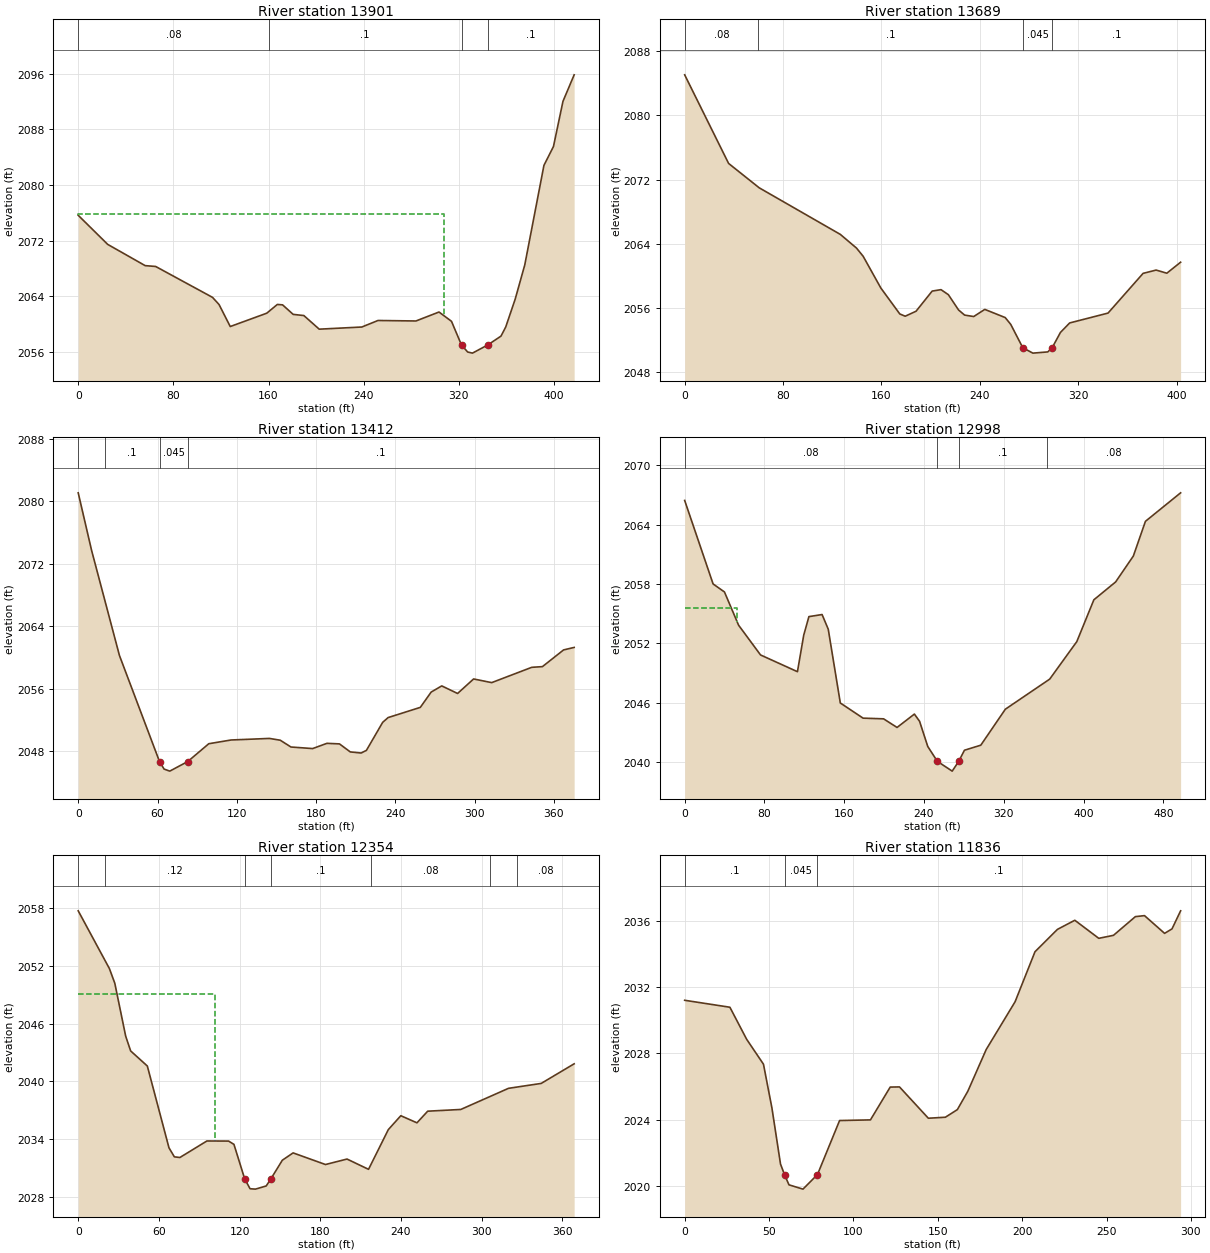
Type RM Length L Ch R = 1 ,13901   ,198.2,212.6,223
XS GIS Cut Line= 3
2203589.89384059661212.3839868852203844.76374875661337.377503734
2203977.53711521661329.735871132
#Sta/Elev= 30
       0 2075.64    24.8 2071.45    56.3 2068.39    65.1 2068.27   112.9 2063.82
   118.4 2062.79   127.8 2059.62   158.5 2061.54   167.4  2062.8   171.8 2062.74
   180.7 2061.37   189.7  2061.2   202.6 2059.24   238.4 2059.55     252 2060.49
   283.9 2060.42   303.3 2061.71   313.8 2060.37  322.22 2056.95   327.4 2055.95
   331.4 2055.79   344.1 2056.95   355.4 2058.24   359.4 2059.56   367.4  2063.6
   375.4  2068.5   391.5 2082.83   399.5 2085.54   407.5 2092.05   416.9 2095.87
#Mann= 4 ,-1,0
       0     .08       0     160      .1       0  322.22    .045       0
   344.1      .1       0
#XS Ineff= 2 , 0
          307.33 2075.81
Permanent Ineff=
       F       F
Bank Sta=322.22,344.1
XS Rating Curve= 0 ,0
Exp/Cntr(USF)=0,0
Exp/Cntr=0.3,0.1

Type RM Length L Ch R = 1 ,13689   ,283.5,276.5,266.8
XS GIS Cut Line= 5
2203528.97789762661273.1166759022203718.67681082661359.347197464
2203729.18405565661400.4209726982203771.21303496661482.568523167
2203821.83885095661515.045461724
#Sta/Elev= 30
       0 2085.06    35.7 2074.02    60.6 2070.98   126.5 2065.18   139.7 2063.47
   145.1 2062.45   159.5 2058.49   174.9 2055.26   179.3 2054.98   188.1  2055.6
   201.2 2058.11   208.4 2058.29   214.4 2057.66   222.7 2055.75   227.6 2055.12
     235 2054.94     244 2055.83   260.6 2054.81   265.1 2053.96   274.9 2051.05
   283.1 2050.38   295.2 2050.53  298.84 2051.07   305.5 2052.96     313 2054.14
   344.2 2055.37   372.7 2060.32   383.3 2060.73     392 2060.34   403.2 2061.71
#Mann= 4 ,-1,0
       0     .08       0      60      .1       0   274.9    .045       0
  298.84      .1       0
Bank Sta=274.9,298.84
XS Rating Curve= 0 ,0
Exp/Cntr(USF)=0,0
Exp/Cntr=0.3,0.1

Type RM Length L Ch R = 1 ,13412   ,413.5,414.5,411.2
XS GIS Cut Line= 4
 2203470.5962283661537.5567403122203592.06045021661578.830990475
2203727.67584361661605.9540691542203836.16815832661598.878483412
#Sta/Elev= 30
       0 2081.11    10.1 2073.75    31.2 2060.27   61.54 2046.67      65 2045.71
    69.3 2045.45    82.9 2046.68    98.8 2048.96   115.7 2049.44   144.7 2049.64
   152.9 2049.41     161 2048.54   177.4 2048.34   188.2 2049.01   197.7 2048.94
   205.9 2047.91   214.1 2047.77   218.1 2048.11   230.4  2051.7   234.5 2052.31
   258.9 2053.62   267.1 2055.58   275.1 2056.37   287.1  2055.4   299.2 2057.26
   312.9 2056.79   343.2 2058.75   351.3 2058.84   367.3 2060.98   375.3  2061.3
#Mann= 4 ,-1,0
       0     .08       0      20      .1       0   61.54    .045       0
    82.9      .1       0
Bank Sta=61.54,82.9
XS Rating Curve= 0 ,0
Exp/Cntr(USF)=0,0
Exp/Cntr=0.3,0.1

Type RM Length L Ch R = 1 ,12998   ,627.3,643.8,656.1
XS GIS Cut Line= 4
2203310.81629161661758.2971498292203462.26666205661936.145637207
 2203618.0813848661971.1301574842203695.45291489662040.860054975
#Sta/Elev= 30
       0 2066.43    28.5    2058    39.9 2057.19    54.1 2053.83    76.1 2050.83
   113.1 2049.14   119.4 2052.83   124.6  2054.7   137.8 2054.91     144 2053.43
   156.1 2045.98   178.9 2044.45   199.5 2044.38     213 2043.51   230.4 2044.86
   235.6 2044.13   243.8 2041.59  253.42 2040.09   268.3  2039.1   274.8 2040.08
   280.6 2041.21     297 2041.72   321.6 2045.35   366.1 2048.39   393.3 2052.18
   410.4  2056.4   432.2  2058.2     450 2060.82   462.1 2064.32   497.4  2067.2
#Mann= 4 ,-1,0
       0     .08       0  253.42    .045       0   274.8      .1       0
   363.6     .08       0
#XS Ineff= 2 , 0
           52.65 2055.62
Permanent Ineff=
       F       F
Bank Sta=253.42,274.8
XS Rating Curve= 0 ,0
Exp/Cntr(USF)=0,0
Exp/Cntr=0.3,0.1

Type RM Length L Ch R = 1 ,12354   ,519.7,517.6,506.8
XS GIS Cut Line= 4
2203172.00108167 661950.115667832203184.41873465662057.098524254
2203176.77710205662225.2144414912203209.25404061662312.138012336
#Sta/Elev= 30
       0 2057.74    23.2 2051.73    27.2 2050.21    35.3  2044.7      39 2043.16
    51.4 2041.59    67.5 2033.08    71.5 2032.14    75.6 2032.07    95.7 2033.79
   111.8 2033.78   115.8 2033.44   123.8 2029.85   127.8 2028.82   131.8 2028.78
   139.8 2029.11  143.34 2029.86   151.8 2031.79   159.8 2032.55   183.9 2031.34
   199.9 2031.91   215.9 2030.84   230.6 2034.97   239.9 2036.42   251.9 2035.68
   259.9 2036.89   284.5 2037.07     320 2039.27   344.3 2039.78   368.8 2041.82
#Mann= 7 ,-1,0
       0      .1       0      20     .12       0   123.8    .045       0
  143.34      .1       0   217.7     .08       0  305.99      .1       0
  325.99     .08       0
#XS Ineff= 2 , 0
          102.08 2049.05
Permanent Ineff=
       F       F
Bank Sta=123.8,143.34
XS Rating Curve= 0 ,0
Exp/Cntr(USF)=0,0
Exp/Cntr=0.3,0.1

Type RM Length L Ch R = 1 ,11836   ,305,309.9,311.5
XS GIS Cut Line= 4
2202730.69679892662089.5754628112202747.89047228662119.186789143
2202849.14210425662253.8705637482202884.48465503662337.928522367
#Sta/Elev= 30
       0  2031.2    26.8 2030.78    36.7 2028.85    46.7 2027.34    51.7  2024.7
    56.8 2021.31   59.19 2020.67    61.8 2020.06    70.1  2019.8    78.7 2020.68
    91.8 2023.94   110.1 2023.98   121.8 2025.96   127.3 2025.97   144.4 2024.08
   154.5 2024.14   161.6  2024.6   167.8 2025.71   178.7 2028.23   195.8 2031.11
   207.6 2034.13   220.9 2035.48   231.2 2036.03   245.4 2034.94   254.1 2035.12
   267.1 2036.25   272.5 2036.31   284.4 2035.24   288.8 2035.51   293.9  2036.6
#Mann= 3 ,-1,0
       0      .1       0   59.19    .045       0    78.7      .1       0
Bank Sta=59.19,78.7
XS Rating Curve= 0 ,0
Exp/Cntr(USF)=0,0
Exp/Cntr=0.3,0.1

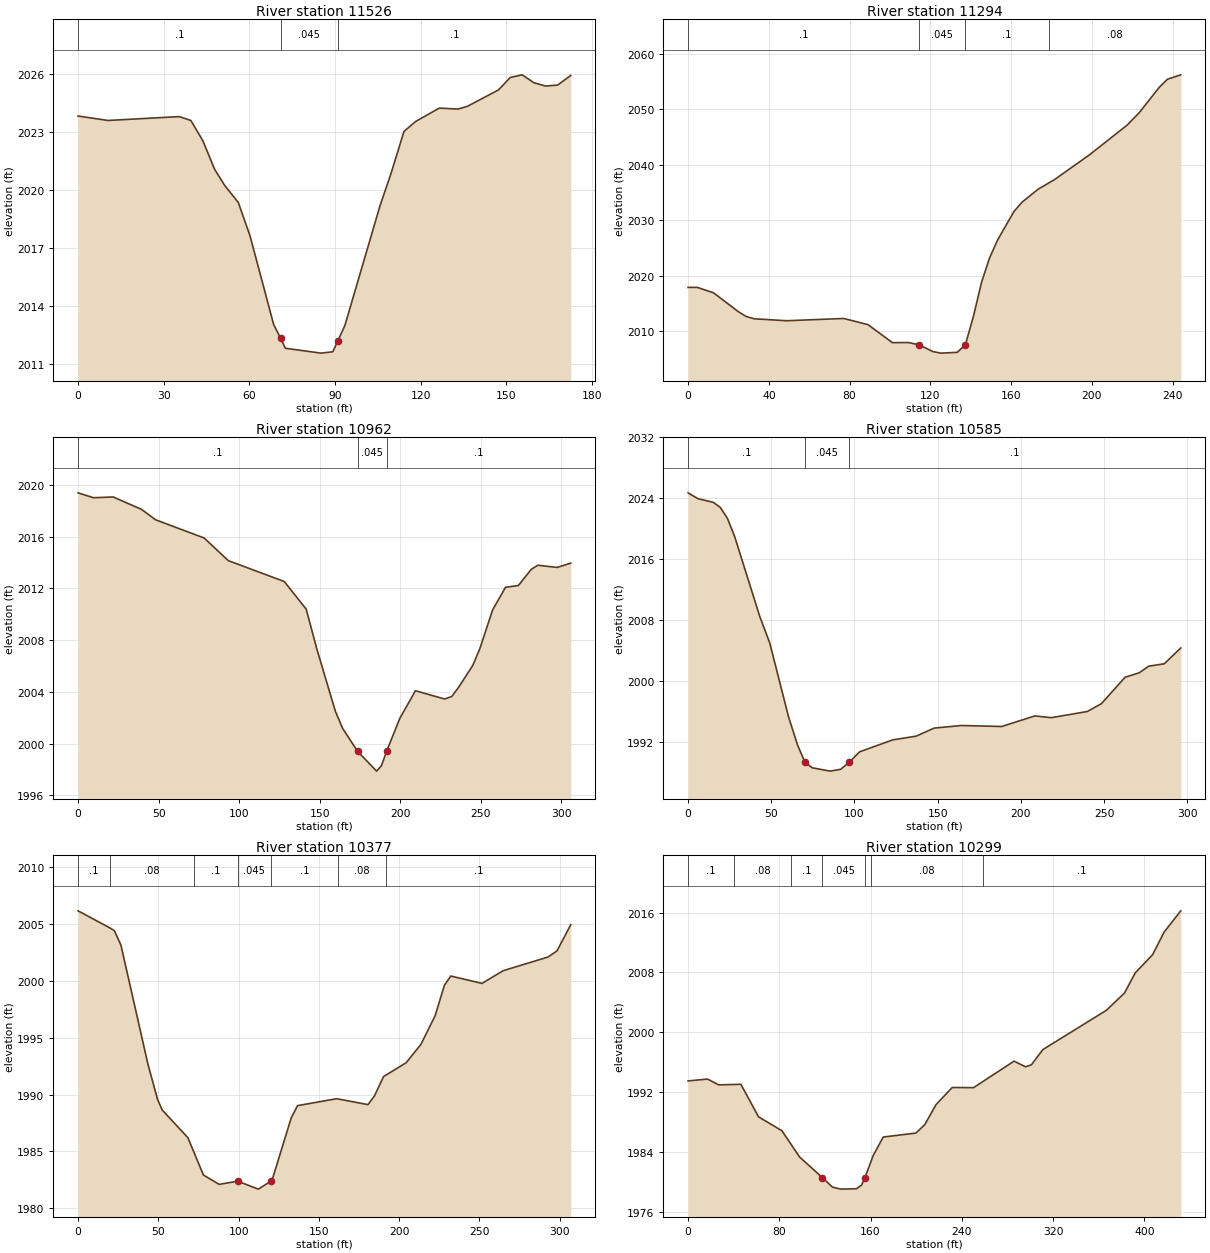
Type RM Length L Ch R = 1 ,11526   ,228.2,232.6,232
XS GIS Cut Line= 2
2202479.51823135662154.9976440132202524.09442153662321.627688245
#Sta/Elev= 30
       0 2023.81    10.5 2023.58    35.4 2023.78    39.5 2023.58    43.7 2022.53
    47.8 2021.06    51.3 2020.23    56.1 2019.34    60.2 2017.62    68.5 2013.02
    70.9 2012.33    72.6  2011.8    85.1 2011.55    89.2 2011.62      912012.199
    93.4 2012.97   105.8 2019.21   109.6 2020.85   114.1 2023.01   118.2 2023.53
   126.5 2024.22     133 2024.17   136.3 2024.31   147.2 2025.16   151.3  2025.8
   155.5 2025.94   159.6 2025.53   163.7 2025.36   167.9 2025.41   172.5 2025.91
#Mann= 3 ,-1,0
       0      .1       0    70.9    .045       0      91      .1       0
Bank Sta=70.9,91
XS Rating Curve= 0 ,0
Exp/Cntr(USF)=0,0
Exp/Cntr=0.3,0.1

Type RM Length L Ch R = 1 ,11294   ,323.9,331.6,336.3
XS GIS Cut Line= 4
2202291.66142989662184.715104131  2202283.170727662246.272700089
2202291.66142989662352.4064862242202289.53875417662427.761474379
#Sta/Elev= 30
       0 2017.88     4.5 2017.89    12.6 2016.91    24.7 2013.56    28.7 2012.65
    32.8 2012.22    48.9 2011.87    77.1 2012.28    89.1 2011.17   101.2 2007.92
   109.2 2007.94  114.52 2007.51   121.2 2006.31   125.2 2006.03   133.3 2006.17
   137.3 2007.52   141.3 2012.63   145.3 2018.75   149.3 2023.19   153.3 2026.44
   161.4 2031.57   165.4 2033.25   173.4  2035.6   181.4  2037.3   198.8 2041.79
   217.4 2047.13   223.4 2049.38   233.4 2053.98   237.4 2055.42     244 2056.21
#Mann= 4 ,-1,0
       0      .1       0  114.52    .045       0   137.3      .1       0
  178.61     .08       0
Bank Sta=114.52,137.3
XS Rating Curve= 0 ,0
Exp/Cntr(USF)=0,0
Exp/Cntr=0.3,0.1

Type RM Length L Ch R = 1 ,10962   ,392.5,376.8,363
XS GIS Cut Line= 4
2202076.20984404662041.434492848  2202030.572316662140.138913954
2201967.95338218662259.0087544252201965.83070646662321.627688245
#Sta/Elev= 30
       0  2019.4     9.6 2019.02    21.8 2019.08    39.4 2018.12    48.2 2017.31
    78.2 2015.91    93.3 2014.15     128 2012.54   141.6  2010.4   148.2 2007.32
   159.7 2002.51   164.2 2001.18   173.5  1999.4   185.3 1997.87   188.3 1998.29
   191.5  1999.4   199.7 2001.95   209.4 2004.09   227.5 2003.45     232 2003.65
   236.5 2004.41     245 2006.05   249.3 2007.32   257.3 2010.34   265.3 2012.09
   273.3 2012.23   281.3 2013.48   285.3  2013.8   297.3 2013.63   305.8 2013.96
#Mann= 3 ,-1,0
       0      .1       0   173.5    .045       0   191.5      .1       0
Bank Sta=173.5,191.5
XS Rating Curve= 0 ,0
Exp/Cntr(USF)=0,0
Exp/Cntr=0.3,0.1

Type RM Length L Ch R = 1 ,10585   ,210.4,208.7,203.9
XS GIS Cut Line= 5
 2201618.7732258661998.9809783952201634.69329372662041.434492848
2201706.86426829662128.4641974792201740.82707985 662176.22440124
 2201791.7712972662236.720659337
#Sta/Elev= 30
       0 2024.71     5.9 2023.94    15.2 2023.46    19.4 2022.78    23.7 2021.33
      28 2018.96    43.2 2008.38    49.1 2004.96    60.4 1995.24    65.8 1991.54
   70.25 1989.29    74.6 1988.55    85.3 1988.11    91.7 1988.35      97  1989.3
     103 1990.64     123 1992.22   137.1 1992.71   147.9 1993.77   164.2 1994.11
   188.5 1993.98   208.4 1995.37   218.3 1995.14   239.9 1995.95   248.4 1996.98
   262.6 2000.45   271.2 2001.05   276.8 2001.91   286.2 2002.23   296.1 2004.31
#Mann= 3 ,-1,0
       0      .1       0   70.25    .045       0      97      .1       0
Bank Sta=70.25,97
XS Rating Curve= 0 ,0
Exp/Cntr(USF)=0,0
Exp/Cntr=0.3,0.1

Type RM Length L Ch R = 1 ,10377   ,80.4,77.3,71.9
XS GIS Cut Line= 4
2201487.17889135662154.9304907292201494.60825638662196.322667322
2201617.72344829662282.291034091 2201716.4278694662340.664616465
#Sta/Elev= 30
       0 2006.18      20 2004.66    22.6 2004.44    26.7 2003.17    43.5  1992.7
    49.5 1989.59    52.4 1988.65    68.4 1986.21    78.1 1982.92    87.9  1982.1
    99.4 1982.38   112.3 1981.68  120.02 1982.37   121.4 1982.72   132.8 1987.96
   136.7 1989.03   161.1 1989.64   180.6 1989.12   184.6 1989.88   190.3 1991.59
   204.4 1992.81   213.6 1994.43   222.4 1996.94   228.2 1999.63   232.2 2000.44
   251.6 1999.79   264.8 2000.91   292.7 2002.11   298.3 2002.65   306.9 2004.96
#Mann= 7 ,-1,0
       0      .1       0      20     .08       0   72.05      .1       0
    99.4    .045       0  120.02      .1       0  162.05     .08       0
  192.05      .1       0
Bank Sta=99.4,120.02
XS Rating Curve= 0 ,0
Exp/Cntr(USF)=0,0
Exp/Cntr=0.3,0.1

Type RM Length L Ch R = 1 ,10299   ,49.8,51,51.3
XS GIS Cut Line= 4
2201382.09526255662217.2030740072201439.87921278662257.298059879
2201544.83373462662312.7234815272201693.73009867662504.715156096
#Sta/Elev= 30
       0 1993.51    17.1 1993.76    26.9 1992.98    46.3 1993.06    61.8 1988.71
    82.3 1986.85    97.8 1983.34   117.8 1980.58   126.7 1979.31     134 1979.05
   147.6  1979.1   152.1 1979.59  155.12 1980.58   162.2  1983.5   171.1 1986.01
   199.7 1986.54   207.5 1987.66   217.4 1990.34   231.6 1992.63   250.3 1992.61
   285.8 1996.15   295.9  1995.4     301 1995.66   311.1  1997.7   366.8 2002.95
   382.7 2005.27   392.1 2007.95   407.3 2010.38   417.4  2013.4     432 2016.24
#Mann= 7 ,-1,0
       0      .1       0      40     .08       0   90.33      .1       0
   117.8    .045       0  155.12      .1       0  160.33     .08       0
  259.02      .1       0
Bank Sta=117.8,155.12
XS Rating Curve= 0 ,0
Exp/Cntr(USF)=0,0
Exp/Cntr=0.3,0.1