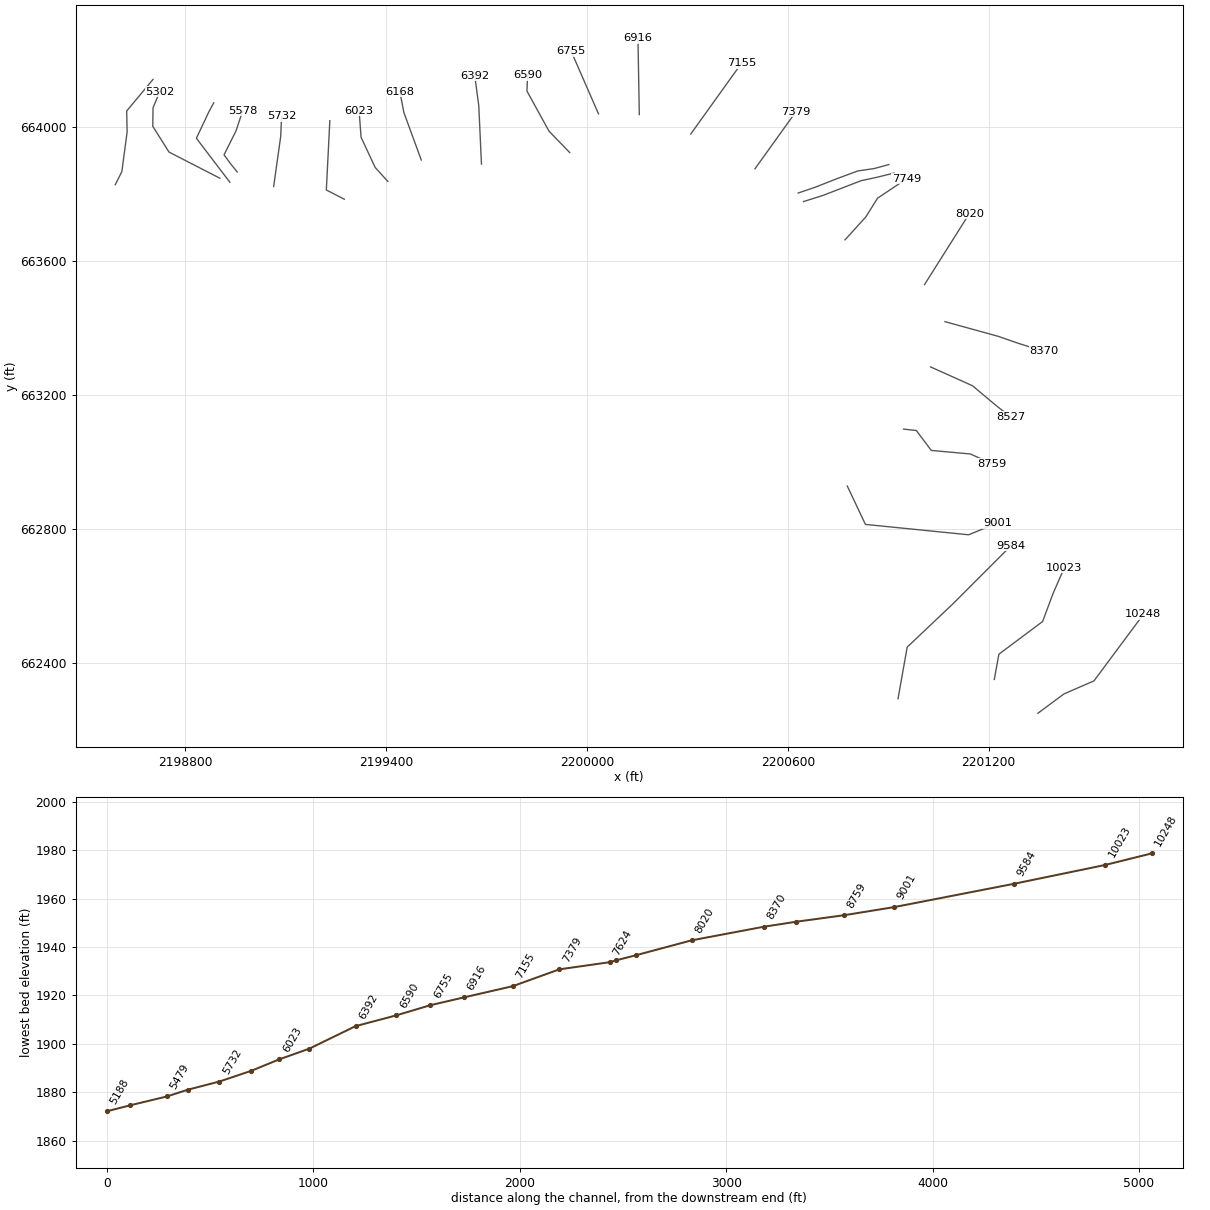
HEC-RAS study PANTHERCK.prj: PANTHERCK

--- PANTHERCK.g01 (geometry) --- (continued)

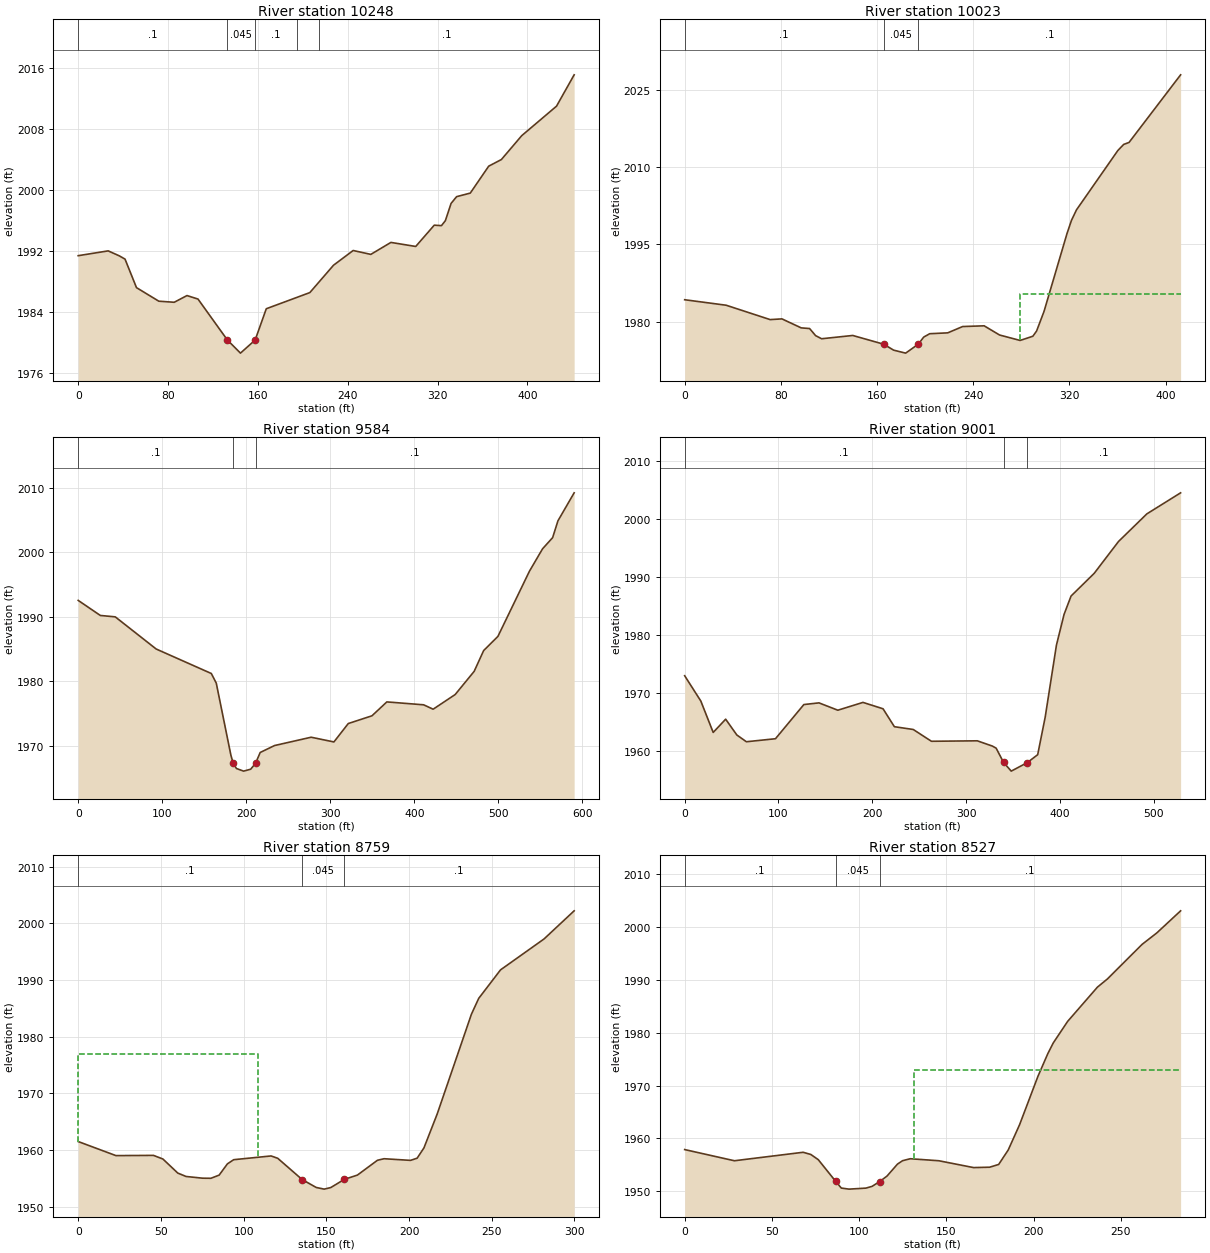
Type RM Length L Ch R = 1 ,10248   ,223.3,225.5,228.4
XS GIS Cut Line= 4
2201346.71733384662250.222474137  2201424.548777662308.006424365
2201514.17286307662346.9221459482201661.55331018 662545.21569317
#Sta/Elev= 30
       0 1991.38    26.7 1992.01    36.7 1991.35    41.7 1990.93    51.9 1987.19
    71.8 1985.41    85.5 1985.27    96.9 1986.15   106.7 1985.69  132.86 1980.32
   144.5  1978.6   157.6 1980.32   167.5 1984.42   206.3 1986.54   227.4 1990.13
   244.9 1992.06   260.6 1991.55   278.5 1993.12   300.6 1992.59   317.1 1995.38
   323.5 1995.32     327 1995.97   332.1 1998.24     337 1999.12   349.2 1999.59
   365.6 2003.12   376.9 2003.99     395 2007.12     426 2010.99   441.7  2015.1
#Mann= 5 ,-1,0
       0      .1       0  132.86    .045       0   157.6      .1       0
  194.64     .08       0  214.64      .1       0
Bank Sta=132.86,157.6
XS Rating Curve= 0 ,0
Exp/Cntr(USF)=0,0
Exp/Cntr=0.3,0.1

Type RM Length L Ch R = 1 ,10023   ,428.3,439.4,439.9
XS GIS Cut Line= 5
 2201216.5377367662351.277995079 2201230.3351289662426.632983234
2201360.87968584662524.2760664782201391.65848382662607.060419664
2201425.62129539662684.538083542
#Sta/Elev= 30
       0 1984.24    34.5 1983.17    71.1 1980.37    80.9 1980.51    96.9 1978.76
   103.9 1978.63   108.9 1977.25   113.9 1976.64   139.8 1977.28   165.5 1975.58
   173.8 1974.42   183.8 1973.84   194.4  1975.6   198.8 1976.96   203.8 1977.62
   218.8 1977.79   231.2 1979.02   249.1 1979.16   261.9 1977.37     279 1976.31
   289.6 1977.13   292.7 1978.14   298.9 1981.97     318 1997.13   321.7  1999.7
   325.9 2001.75   360.3 2013.31   365.2  2014.5   369.6 2014.88   412.5 2028.05
#Mann= 3 ,-1,0
       0      .1       0   165.5    .045       0   194.4      .1       0
#XS Ineff= 2 , 0
                           278.9         1985.42
Permanent Ineff=
       F       F
Bank Sta=165.5,194.4
XS Rating Curve= 0 ,0
Exp/Cntr(USF)=0,0
Exp/Cntr=0.3,0.1

Type RM Length L Ch R = 1 ,9584    ,592.9,582.5,570.3
XS GIS Cut Line= 4
2200929.06578796662293.7734375172200956.50996067662447.859740461
2201094.48388265662578.404297407 2201266.7479823662750.803450126
#Sta/Elev= 30
       0 1992.55    26.3 1990.22    44.1    1990    92.8 1985.02   158.4 1981.23
   164.3 1979.74   181.7 1968.58  184.41 1967.33   188.3 1966.52   196.8 1966.11
   205.3 1966.41   211.1 1967.34   216.6    1969   233.6 1970.07   277.2 1971.36
   304.3 1970.63   321.4 1973.48   349.6 1974.68   367.3 1976.83   411.1 1976.38
   422.4  1975.7   448.6 1977.97   471.2 1981.56   482.5 1984.78   499.5 1986.98
     537 1997.07   552.6 2000.54   564.6 2002.27   570.9 2004.87   590.2 2009.21
#Mann= 3 ,-1,0
       0      .1       0  184.41    .045       0   211.1      .1       0
Bank Sta=184.41,211.1
XS Rating Curve= 0 ,0
Exp/Cntr(USF)=0,0
Exp/Cntr=0.3,0.1

Type RM Length L Ch R = 1 ,9001    ,241.7,241.9,241.8
XS GIS Cut Line= 4
2200777.61370283662928.692494886 2200831.7737739662814.182630349
2201139.71246367662783.2340183122201225.59486207662818.051206854
#Sta/Elev= 30
       0 1972.95    17.2 1968.58    30.4 1963.15    43.7 1965.44    55.6 1962.71
    65.8 1961.54    96.8 1962.06   127.1 1967.97   143.2 1968.26   163.3 1966.99
   190.1 1968.34   211.5 1967.24   223.6 1964.14   243.7 1963.66   263.1 1961.62
     312  1961.7   328.1 1960.79   332.1 1960.43  340.01 1957.97   348.2 1956.46
   365.4 1957.94   376.4  1959.3   384.4 1965.79   396.4 1978.25   404.5 1983.54
     412 1986.73   436.7 1990.66   462.6 1996.16   492.8 2000.93   528.8 2004.57
#Mann= 3 ,-1,0
       0      .1       0  340.01    .045       0   365.4      .1       0
Bank Sta=340.01,365.4
XS Rating Curve= 0 ,0
Exp/Cntr(USF)=0,0
Exp/Cntr=0.3,0.1

Type RM Length L Ch R = 1 ,8759    ,233.9,232.2,224.7
XS GIS Cut Line= 5
2200945.55689567 663098.829773642200983.76505868663094.584422194
2201028.34124886663035.149501959 2201145.0884136663024.536123345
2201208.76868528662995.880001089
#Sta/Elev= 30
       0 1961.51    22.8 1959.03    45.5 1959.07    51.2 1958.43    60.2 1955.95
    65.2 1955.35    75.2 1955.05    80.2 1955.03    85.2 1955.59    90.2 1957.58
      94 1958.31   116.6 1958.97   120.6 1958.56  135.38 1954.81   143.9 1953.41
   148.7 1953.12   152.7  1953.4   160.8 1954.83   168.8  1955.6   180.9 1958.21
   184.9 1958.48   200.9 1958.19   204.9 1958.58     209 1960.39     217 1966.36
   237.7 1983.96   242.1 1986.75   255.3 1991.78   281.6 1997.23   299.8 2002.19
#Mann= 3 ,-1,0
       0      .1       0  135.38    .045       0   160.8      .1       0
#XS Ineff= 2 , 0
          108.68 1976.98
Permanent Ineff=
       F       F
Bank Sta=135.38,160.8
XS Rating Curve= 0 ,0
Exp/Cntr(USF)=0,0
Exp/Cntr=0.3,0.1

Type RM Length L Ch R = 1 ,8527    ,155.5,157.4,159.4
XS GIS Cut Line= 4
2201026.21857313663284.5638993762201151.45644077663228.312992724
2201217.25938818663173.1234239342201265.01959194663134.915260926
#Sta/Elev= 30
       0  1957.9    28.5 1955.79    67.9 1957.39    72.3 1956.98    76.6 1955.99
   86.61 1951.88    89.8 1950.63    94.2 1950.43   103.9 1950.62   107.4 1950.95
   111.8 1951.86     116  1952.9     122 1955.16   124.9  1955.8   129.3 1956.17
   145.7 1955.79   165.6  1954.5   174.8 1954.57     180 1955.09   185.5 1957.84
     192 1962.61   202.5 1971.73   208.2 1976.04   211.3 1978.05   219.5  1982.1
   236.6 1988.58   242.3 1990.12   262.2 1996.66   270.7 1998.84   284.3    2003
#Mann= 3 ,-1,0
       0      .1       0   86.61    .045       0   111.8      .1       0
#XS Ineff= 2 , 0
                          131.49         1972.91
Permanent Ineff=
       F       F
Bank Sta=86.61,111.8
XS Rating Curve= 0 ,0
Exp/Cntr(USF)=0,0
Exp/Cntr=0.3,0.1

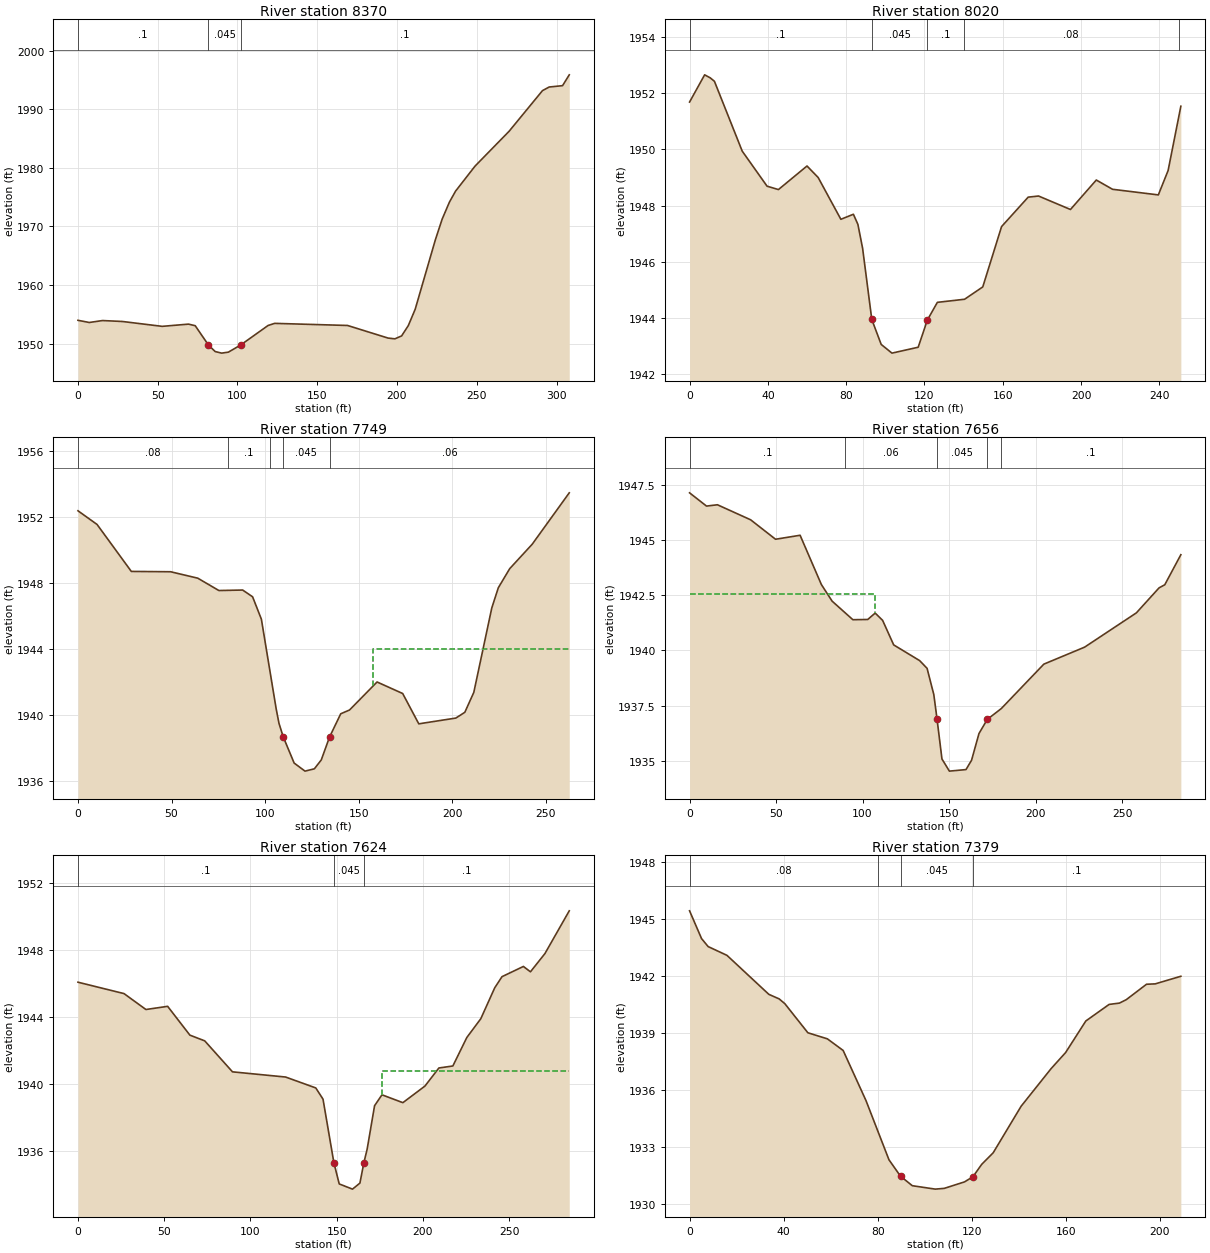
Type RM Length L Ch R = 1 ,8370    ,331.8,350.1,362.9
XS GIS Cut Line= 4
2201069.30693619663419.6575775132201228.34841471663375.813710461
2201290.24563878663354.321618768 2201364.1784342663331.110159741
#Sta/Elev= 30
       0 1953.96     7.1 1953.59    15.4 1953.92    27.9 1953.76    52.8 1952.93
    69.3 1953.31    73.5 1953.04    81.8 1949.74      86 1948.63    90.1 1948.36
    94.3 1948.53   101.9 1949.73   119.2 1953.08   123.3 1953.44     169 1953.08
   194.4 1950.93   198.7  1950.8   202.9  1951.3   207.1 1953.06   211.4 1955.84
   224.1 1967.74   228.3 1971.22   232.9 1974.15   236.7    1976   248.9 1980.27
   270.3 1986.23   291.2 1993.16   295.4 1993.78   303.8 1994.01     308 1995.86
#Mann= 3 ,-1,0
       0      .1       0    81.8    .045       0   101.9      .1       0
Bank Sta=81.8,101.9
XS Rating Curve= 0 ,0
Exp/Cntr(USF)=0,0
Exp/Cntr=0.3,0.1

Type RM Length L Ch R = 1 ,8020    ,266.5,270.7,267
XS GIS Cut Line= 2
2201008.27532592663530.4271813092201142.29086268663742.618447844
#Sta/Elev= 30
       0 1951.69     7.7 1952.66    10.6 1952.55    12.7 1952.43    26.9 1949.94
    39.6 1948.69    45.4 1948.57      60 1949.41    65.7    1949    77.3 1947.51
    83.7 1947.69      86 1947.33    88.4 1946.48    93.1 1943.94    97.9 1943.05
   103.4 1942.74   116.8 1942.95   121.5 1943.92   126.6 1944.55   140.5 1944.66
   149.8  1945.1   159.4 1947.25     173  1948.3   178.3 1948.34   194.6 1947.86
   207.8 1948.91   216.1 1948.58   239.5 1948.38   244.5 1949.25     251 1951.54
#Mann= 5 ,-1,0
       0      .1       0    93.1    .045       0   121.5      .1       0
     140     .08       0     250     .06       0
Bank Sta=93.1,121.5
XS Rating Curve= 0 ,0
Exp/Cntr(USF)=0,0
Exp/Cntr=0.3,0.1

Type RM Length L Ch R = 1 ,7749    ,101.2,93.2,84.3
XS GIS Cut Line= 4
2200770.92088833663664.0381570132200833.08063158663732.545375062
2200867.99952989663788.4156123482200954.62742188663846.187599856
#Sta/Elev= 30
       0 1952.37    10.2 1951.54    28.5 1948.69    49.5 1948.67      64 1948.28
    75.3 1947.53      88 1947.56    93.3 1947.15      98 1945.79   105.9 1940.35
   107.4 1939.47   109.7 1938.64   115.5 1937.06   121.3 1936.57   126.3 1936.71
     130 1937.25  134.42 1938.64   140.4 1940.05   145.1 1940.28   159.8 1941.98
   173.5 1941.28   182.1 1939.44   201.9 1939.79   206.7 1940.14   211.5 1941.35
   221.1 1946.47   224.6  1947.7   230.7 1948.86   242.7 1950.34   262.5 1953.46
#Mann= 5 ,-1,0
       0     .08       0      80      .1       0   102.5     .06       0
   109.7    .045       0  134.42     .06       0
#XS Ineff= 2 , 0
                           157.7         1944.01
Permanent Ineff=
       F       F
Bank Sta=109.7,134.42
XS Rating Curve= 0 ,0
Exp/Cntr(USF)=0,0
Exp/Cntr=0.3,0.1

Type RM Length L Ch R = 1 ,7656    ,31.3,31.4,33.3
XS GIS Cut Line= 5
2200646.83944209663778.261976731 2200704.1516866663796.304720373
 2200819.4326339663840.845252322 2200865.3846633663850.572916293
 2200917.1404146663863.466087902
#Sta/Elev= 30
       0 1947.13     9.8 1946.53    16.1 1946.59    35.3 1945.91    49.7 1945.03
    63.9 1945.21    76.2 1942.98    82.4 1942.23    94.4 1941.39     103  1941.4
   107.3 1941.69   111.6 1941.36     118 1940.25     133 1939.54   137.3 1939.19
   141.2    1938  143.05  1936.9   145.9 1935.09   150.2 1934.54   159.8 1934.61
     163 1935.03   167.3 1936.24   172.1 1936.88   180.2 1937.37   204.8 1939.38
   228.4 1940.15   258.3  1941.7   271.4 1942.83   274.7 1942.97     284 1944.33
#Mann= 5 ,-1,0
       0      .1       0   90.09     .06       0  143.05    .045       0
   172.1     .06       0  180.09      .1       0
#XS Ineff= 2 , 0
          107.11 1942.55
Permanent Ineff=
       F       F
Bank Sta=143.05,172.1
XS Rating Curve= 0 ,0
Exp/Cntr(USF)=0,0
Exp/Cntr=0.3,0.1

Type RM Length L Ch R = 1 ,7624    ,243.8,245.5,250.5
XS GIS Cut Line= 6
2200630.91937417663803.7340854032200680.80225366663820.715491184
 2200745.5438632663846.1875998562200808.71590327663869.611213495
2200858.74319305663877.0632629572200901.88773715663888.834844555
#Sta/Elev= 30
       0  1946.1    26.7 1945.42    39.4 1944.47      52 1944.66    64.9 1942.94
    73.5  1942.6    89.6 1940.75   120.4 1940.44   137.9 1939.79   142.1 1939.12
   148.4 1935.33   151.5 1934.06   159.2 1933.75   163.5 1934.11  165.81 1935.33
   167.7 1936.14     172 1938.73   176.3 1939.38   188.4 1938.91   201.2  1939.9
   209.3 1940.98   217.4  1941.1   225.5  1942.8   233.6 1943.92   241.7 1945.77
   245.9 1946.43   258.3 1947.04   262.4 1946.72   270.8 1947.81   284.9 1950.36
#Mann= 3 ,-1,0
       0      .1       0   148.4    .045       0  165.81      .1       0
#XS Ineff= 2 , 0
                          176.41         1940.83
Permanent Ineff=
       F       F
Bank Sta=148.4,165.81
XS Rating Curve= 0 ,0
Exp/Cntr(USF)=0,0
Exp/Cntr=0.3,0.1

Type RM Length L Ch R = 1 ,7379    ,220.9,223.5,222.4
XS GIS Cut Line= 2
2200501.98796871663876.2775041732200623.81072898664046.030530781
#Sta/Elev= 30
       0 1945.41     5.1 1943.95     7.9 1943.53    15.9 1943.07    33.7 1941.02
    38.1 1940.78    40.5 1940.53    50.3    1939    58.6 1938.68    65.3 1938.07
      75 1935.44    84.8 1932.32    89.7 1931.46    94.7 1930.96   104.5 1930.78
   108.3 1930.82   116.9 1931.16  120.49 1931.43   124.2 1932.08   129.1 1932.69
     141 1935.14   153.7 1937.11   159.9 1937.96   168.5 1939.62   178.4 1940.49
   182.8 1940.56   185.7 1940.74   194.3 1941.55     198 1941.57   208.9 1941.97
#Mann= 4 ,-1,0
       0     .08       0      80      .1       0    89.7    .045       0
  120.49      .1       0
Bank Sta=89.7,120.49
XS Rating Curve= 0 ,0
Exp/Cntr(USF)=0,0
Exp/Cntr=0.3,0.1

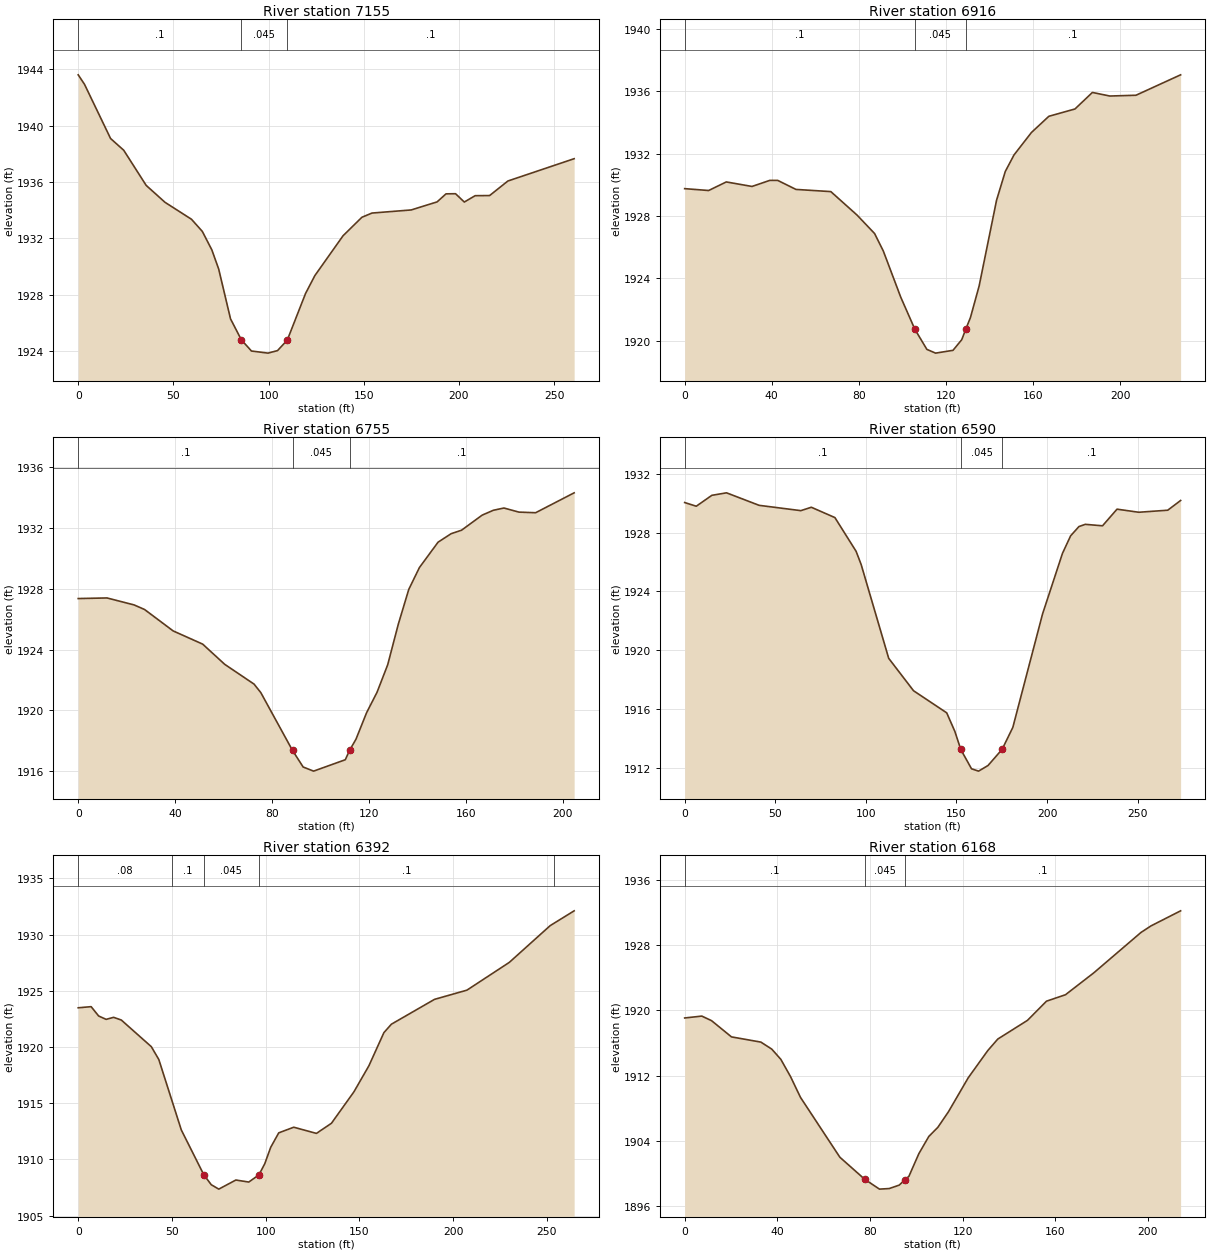
Type RM Length L Ch R = 1 ,7155    ,233.7,238.9,248.4
XS GIS Cut Line= 2
2200310.26690336663980.1264145692200462.04608009 664191.81842422
#Sta/Elev= 30
       0 1943.59     3.3 1942.92      17 1939.08    23.9 1938.25    35.7 1935.76
    45.6 1934.56    59.5 1933.36    65.2  1932.5    70.2 1931.19    73.8 1929.83
      80 1926.31    85.7 1924.82      91 1924.03    99.7 1923.88   104.7 1924.06
  109.81  1924.8   119.4  1928.1   124.3 1929.37   139.1 1932.19     149  1933.5
   154.3  1933.8   174.9 1934.02   188.5 1934.59   193.2 1935.16   198.2 1935.17
   202.8 1934.58   208.5 1935.03   216.1 1935.04   225.7 1936.07   260.5 1937.65
#Mann= 3 ,-1,0
       0      .1       0    85.7    .045       0  109.81      .1       0
Bank Sta=85.7,109.81
XS Rating Curve= 0 ,0
Exp/Cntr(USF)=0,0
Exp/Cntr=0.3,0.1

Type RM Length L Ch R = 1 ,6916    ,158.3,161.7,167.5
XS GIS Cut Line= 2
 2200156.4906322664038.0421530582200152.49644334664265.710918155
#Sta/Elev= 30
       0 1929.75      11 1929.63    19.1 1930.18    30.9 1929.89    39.1 1930.28
    42.7 1930.28    51.1  1929.7    67.1 1929.56    79.1 1928.06    87.2 1926.87
    91.2 1925.75    99.2 1922.79  105.72 1920.72   111.2 1919.44   115.2  1919.2
   123.2 1919.38   127.2 1920.06   129.1 1920.75   131.2 1921.48   135.2 1923.51
   143.2 1929.01   147.2 1930.85   151.2 1931.91   159.2 1933.35   167.2 1934.39
   179.2 1934.86   187.2 1935.92   195.2 1935.69   207.2 1935.74   227.7 1937.05
#Mann= 3 ,-1,0
       0      .1       0  105.72    .045       0   129.1      .1       0
Bank Sta=105.72,129.1
XS Rating Curve= 0 ,0
Exp/Cntr(USF)=0,0
Exp/Cntr=0.3,0.1

Type RM Length L Ch R = 1 ,6755    ,163.9,165.3,165.9
XS GIS Cut Line= 2
2200034.66787193664040.0392474892199952.78700027664227.766123972
#Sta/Elev= 30
       0 1927.36    11.9  1927.4    23.1 1926.94    27.4 1926.64    39.2 1925.23
    51.4 1924.36    60.5 1923.03    72.6 1921.73    75.4 1921.17    88.5 1917.36
    92.9 1916.27    97.2    1916   110.3 1916.75  112.07 1917.37   114.7  1918.1
   119.1 1919.85   123.4 1921.19   127.8    1923   132.2 1925.68   136.5 1927.96
   140.9  1929.4   148.6 1931.07     154 1931.63   158.3 1931.86   166.8 1932.85
   171.4 1933.17   175.8 1933.32     182 1933.05   188.9 1933.01   204.8 1934.32
#Mann= 3 ,-1,0
       0      .1       0    88.5    .045       0  112.07      .1       0
Bank Sta=88.5,112.07
XS Rating Curve= 0 ,0
Exp/Cntr(USF)=0,0
Exp/Cntr=0.3,0.1

Type RM Length L Ch R = 1 ,6590    ,199.8,197.3,185.7
XS GIS Cut Line= 4
2199948.79341285663924.564523964 2199886.8834855663988.471545746
2199820.97936928664108.2972115872199822.97646371664156.227477923
#Sta/Elev= 30
       0 1930.04     6.4 1929.79      15 1930.53    23.1  1930.7    41.1 1929.85
    64.1 1929.49    69.9 1929.72    82.9 1929.02    94.6 1926.73    97.4 1925.83
   112.6 1919.46   126.3 1917.26   144.6 1915.76   149.1  1914.5  152.38 1913.27
   158.3 1911.96   162.2  1911.8   167.4 1912.18   175.2 1913.28   181.1 1914.77
   197.5 1922.47   208.5 1926.59     213 1927.78   217.6 1928.41   221.1 1928.56
   230.6 1928.46   238.6 1929.59   250.6 1929.38   266.6 1929.52   273.7 1930.18
#Mann= 3 ,-1,0
       0      .1       0  152.38    .045       0   175.2      .1       0
Bank Sta=152.38,175.2
XS Rating Curve= 0 ,0
Exp/Cntr(USF)=0,0
Exp/Cntr=0.3,0.1

Type RM Length L Ch R = 1 ,6392    ,218.9,223.7,218.7
XS GIS Cut Line= 3
2199685.17634656663890.2571651882199677.18796884664064.004380657
2199665.20540225664153.873630037
#Sta/Elev= 30
       0 1923.49     6.9 1923.59    10.9 1922.76    14.9 1922.46    18.9 1922.64
      23  1922.4      39 1920.03      43 1918.89      55 1912.62      67 1908.63
      71 1907.74      75 1907.35    84.1 1908.16      91 1907.98   96.41 1908.62
    99.5  1909.6   102.7 1911.07     107 1912.36     115 1912.86   127.1 1912.31
   135.1 1913.21   147.1 1916.01   155.1 1918.33   163.1 1921.28   167.1 1922.03
   190.1 1924.24   207.4 1925.06     230 1927.53   251.8  1930.8   264.6 1932.12
#Mann= 5 ,-1,0
       0     .08       0      50      .1       0      67    .045       0
   96.41      .1       0  253.93     .05       0
Bank Sta=67,96.41
XS Rating Curve= 0 ,0
Exp/Cntr(USF)=0,0
Exp/Cntr=0.3,0.1

Type RM Length L Ch R = 1 ,6168    ,144.3,145.1,145.5
XS GIS Cut Line= 3
 2199505.4378478663902.239731772 2199453.5133926 664044.03343635
2199441.53082602664105.943363701
#Sta/Elev= 30
       0 1919.07     7.4  1919.3    11.6 1918.74    20.2 1916.75    32.9 1916.11
    37.6 1915.25    41.5    1914    45.7 1911.88      50 1909.33      67 1901.99
    77.71899.293    84.1 1898.08    88.3 1898.15    92.6 1898.57    95.11899.233
    96.8 1899.65   101.1 1902.43   105.4 1904.54   109.3 1905.66   113.9 1907.58
   122.4 1911.73   130.9 1915.09   135.2 1916.49     148 1918.78   156.2 1921.13
   164.4 1921.92   176.6  1924.6     197 1929.56   201.3 1930.36   214.1 1932.21
#Mann= 3 ,-1,0
       0      .1       0    77.7    .045       0    95.1      .1       0
Bank Sta=77.7,95.1
XS Rating Curve= 0 ,0
Exp/Cntr(USF)=0,0
Exp/Cntr=0.3,0.1

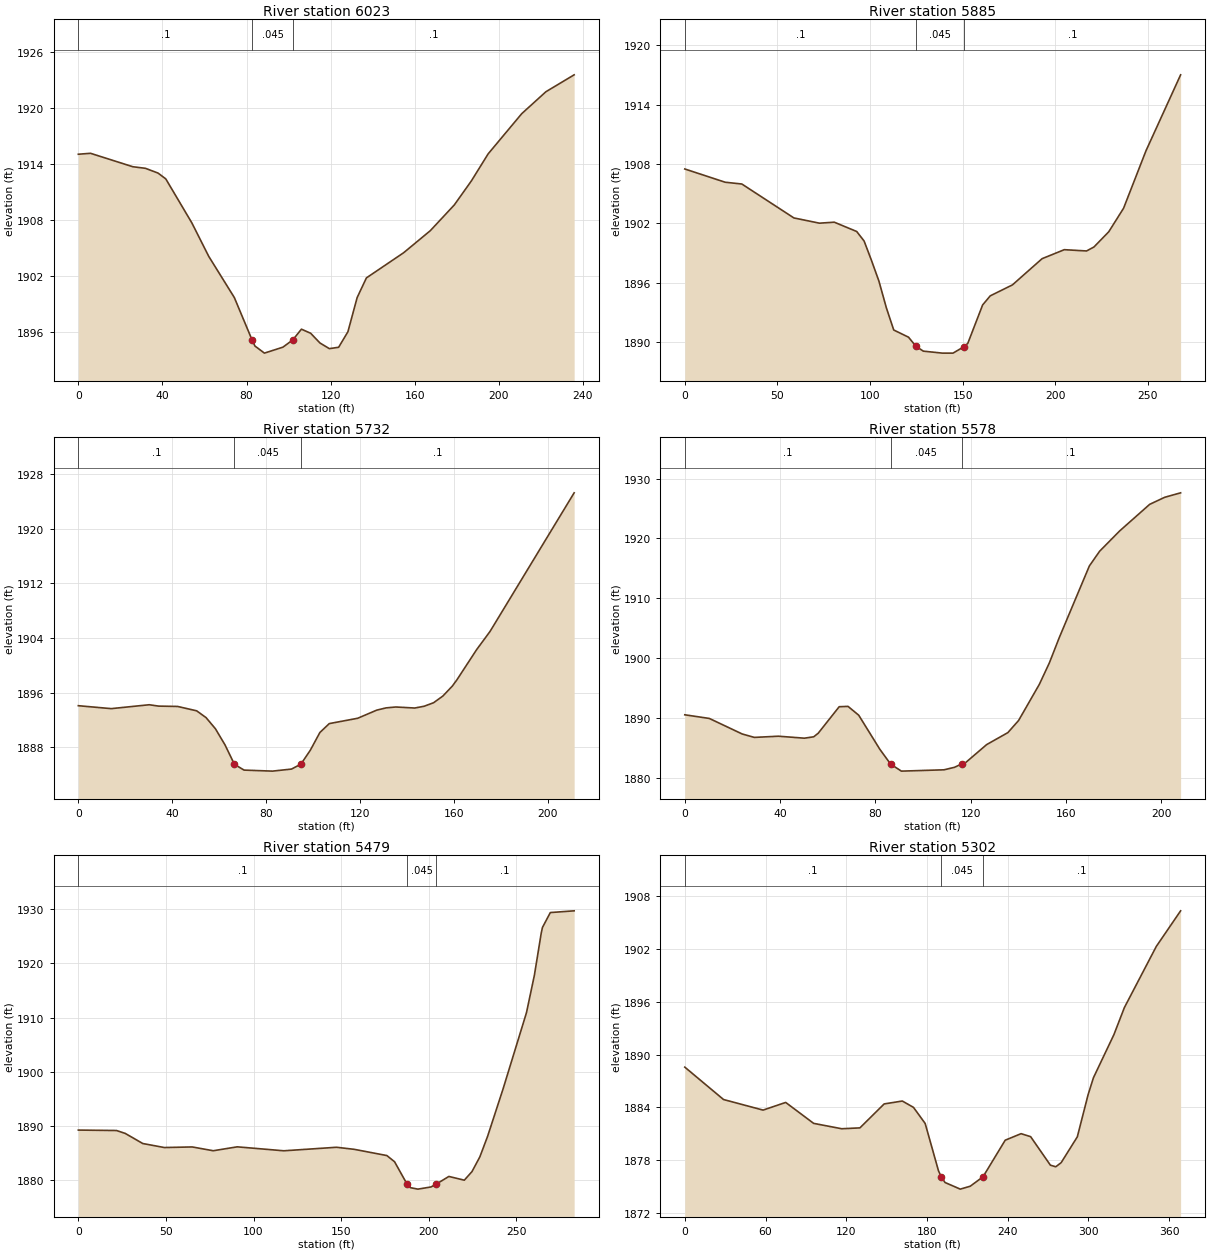
Type RM Length L Ch R = 1 ,6023    ,142.1,138.2,130.9
XS GIS Cut Line= 4
2199405.58312627 663838.332709992199367.63833208663880.271693035
2199325.69934904663970.1409424152199319.70806575664050.024719642
#Sta/Elev= 30
       0 1915.02     5.8 1915.12    25.9 1913.68    31.9 1913.51    37.9    1913
    41.6 1912.37      54 1907.65      62 1904.07    74.2 1899.64   82.72 1895.04
      84 1894.44    88.5 1893.68    97.3 1894.32     102  1895.1   106.1 1896.25
   110.5 1895.81   114.9 1894.77   119.4 1894.16   123.8 1894.31   128.2 1895.97
   132.6 1899.64     137 1901.75   154.7 1904.45   167.4 1906.82   178.8 1909.58
   186.9 1912.15   194.9 1915.06   210.9 1919.38   222.4 1921.73   235.8 1923.54
#Mann= 3 ,-1,0
       0      .1       0   82.72    .045       0     102      .1       0
Bank Sta=82.72,102
XS Rating Curve= 0 ,0
Exp/Cntr(USF)=0,0
Exp/Cntr=0.3,0.1

Type RM Length L Ch R = 1 ,5885    ,153.4,152.7,151
XS GIS Cut Line= 3
2199275.61718573663785.3038254682199221.89514584663812.819992244
2199232.37749509664019.846389886
#Sta/Elev= 30
       0 1907.49    21.8 1906.15    30.8 1905.97    58.9 1902.54    72.7 1902.01
    80.7 1902.11    92.8 1901.17    96.8 1900.21   100.8 1898.24   104.8 1896.16
   108.8 1893.47   112.8 1891.21   120.8 1890.48   124.8 1889.56   128.8 1889.07
   139.1 1888.87   144.8 1888.87  150.94 1889.54   152.8 1889.86   160.8 1893.74
   164.9 1894.66   176.9 1895.77   192.9 1898.42   204.9 1899.33   216.9  1899.2
   220.9  1899.6   228.9 1901.14   236.9 1903.52     249 1909.33   267.7 1917.01
#Mann= 3 ,-1,0
       0      .1       0   124.8    .045       0  150.94      .1       0
Bank Sta=124.8,150.94
XS Rating Curve= 0 ,0
Exp/Cntr(USF)=0,0
Exp/Cntr=0.3,0.1

Type RM Length L Ch R = 1 ,5732    ,158,154.6,148.2
XS GIS Cut Line= 3
2199064.65990712663823.3023414912199085.62460562663972.675818271
2199088.24519293664032.949326446
#Sta/Elev= 30
       0 1894.08      14 1893.65    30.2 1894.22    34.2 1894.02    42.3 1893.97
    50.4 1893.33    54.4 1892.34    58.4  1890.7    62.5 1888.33    66.5 1885.49
    70.6 1884.65    82.7  1884.5    90.8  1884.8    94.8 1885.52    98.8 1887.55
   102.9 1890.16   106.9 1891.46     119 1892.24   127.1 1893.43   131.1 1893.76
   135.2 1893.89   143.3 1893.74   147.3    1894   151.3 1894.51   155.3  1895.5
   159.3 1896.95   161.3 1897.89   169.6 1902.26   175.4 1904.97   211.2 1925.25
#Mann= 3 ,-1,0
       0      .1       0    66.5    .045       0    94.8      .1       0
Bank Sta=66.5,94.8
XS Rating Curve= 0 ,0
Exp/Cntr(USF)=0,0
Exp/Cntr=0.3,0.1

Type RM Length L Ch R = 1 ,5578    ,98.4,99,98.9
XS GIS Cut Line= 5
2198955.96023687663866.4840714292198934.65211748663892.805865966
2198916.47754506663917.874241716 2198952.1999805663989.319112602
 2198972.2546811664049.483214401
#Sta/Elev= 30
       0 1890.51    10.3  1889.9    24.1  1887.3    29.2 1886.73    39.3 1886.93
    50.2  1886.6    54.1 1886.83      56 1887.43    64.8 1891.86    68.5 1891.92
      73 1890.44    81.9 1884.72    86.4 1882.26    90.9 1881.09   108.8 1881.31
   113.2 1881.73  116.27  1882.3   117.7 1882.46   126.7 1885.53   135.6 1887.53
   140.1 1889.56   148.8  1895.6     153 1899.18   157.2 1903.45   169.8  1915.4
   174.1 1917.86   182.5 1921.25   195.1  1925.7   201.4 1926.88   208.1 1927.63
#Mann= 3 ,-1,0
       0      .1       0    86.4    .045       0  116.27      .1       0
Bank Sta=86.4,116.27
XS Rating Curve= 0 ,0
Exp/Cntr(USF)=0,0
Exp/Cntr=0.3,0.1

Type RM Length L Ch R = 1 ,5479    ,163.5,177.5,183.5
XS GIS Cut Line= 4
 2198933.9099318663835.8572073372198833.89974937663967.323450054
2198871.76215491664047.5296699582198885.68903032664073.062274888
#Sta/Elev= 30
       0 1889.24    21.8 1889.16    26.8 1888.62    36.8 1886.76    49.1 1886.02
      65 1886.13      77 1885.43    90.7 1886.15   117.3 1885.42   147.4 1886.07
   157.5 1885.69   176.1 1884.54   180.5  1883.4  187.56 1879.31   189.4 1878.63
   193.8 1878.35   201.3 1878.75   204.3 1879.28   211.5 1880.69   220.3    1880
   224.7 1881.59   229.2 1884.32   233.6 1888.09   242.4 1896.81   255.8 1910.91
   260.3  1917.8   264.2 1925.55   264.9 1926.61   269.4 1929.36     283 1929.68
#Mann= 3 ,-1,0
       0      .1       0  187.56    .045       0   204.3      .1       0
Bank Sta=187.56,204.3
XS Rating Curve= 0 ,0
Exp/Cntr(USF)=0,0
Exp/Cntr=0.3,0.1

Type RM Length L Ch R = 1 ,5302    ,123.2,113.5,101.8
XS GIS Cut Line= 5
2198903.94909009663848.0138934542198752.16142017663926.024811802
2198703.68343836664002.9972186782198704.45715366664058.704720344
2198724.57375149  664105.9013537
#Sta/Elev= 30
       0 1888.58    28.8  1884.9    58.2  1883.7      75 1884.57    95.8 1882.19
   116.7 1881.58   130.2 1881.68   148.2  1884.4   161.7 1884.73     170 1884.01
   178.7 1882.18   188.6  1876.8  190.77 1876.08   193.5 1875.47   204.8 1874.72
   212.2 1875.05   221.7 1876.12   238.2 1880.28     250 1881.02   257.1 1880.68
   271.8 1877.44   275.8 1877.26   279.8 1877.73   291.8 1880.66   299.8 1885.44
   303.8 1887.38     319 1892.27   326.8 1895.35   350.5 1902.29   368.6 1906.34
#Mann= 3 ,-1,0
       0      .1       0  190.77    .045       0   221.7      .1       0
Bank Sta=190.77,221.7
XS Rating Curve= 0 ,0
Exp/Cntr(USF)=0,0
Exp/Cntr=0.3,0.1

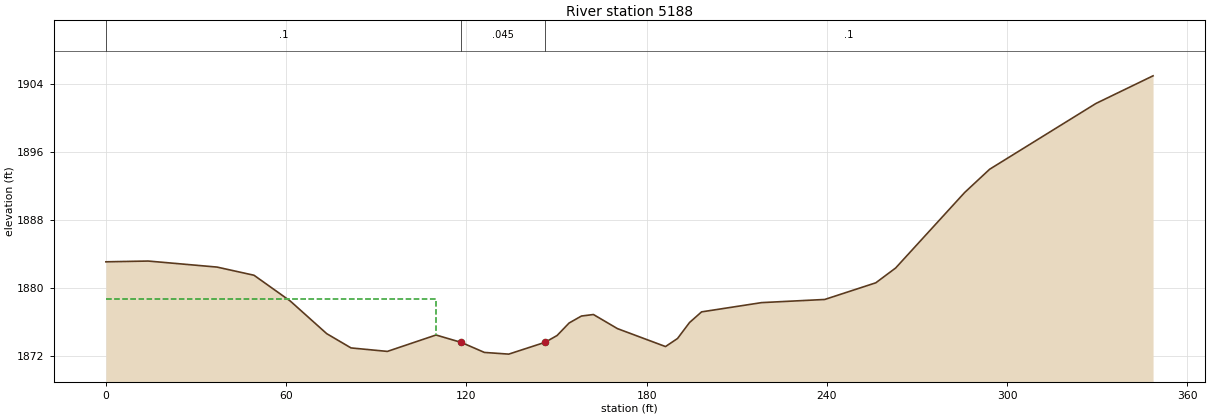
Type RM Length L Ch R = 1 ,5188    ,230.6,225.3,216.5
XS GIS Cut Line= 5
2198591.64389732663828.5435161152198611.29830216663867.852325794
2198627.02182603663985.7787548312198625.71153237664048.672850318
2198704.32915173664143.013993547
#Sta/Elev= 30
       0  1883.1    14.1 1883.19      37 1882.48    49.3 1881.52    61.4 1878.48
    73.5 1874.65    81.6 1872.97    93.7 1872.56   109.9 1874.49  118.37 1873.61
     126 1872.44   134.1 1872.24   146.2 1873.63   150.2 1874.43   154.2  1875.9
   158.3 1876.72   162.3  1876.9   170.3 1875.24   186.3 1873.13   190.3 1874.08
   194.3 1875.96   198.3 1877.21   218.3  1878.3   239.3 1878.67   256.3 1880.63
   262.9 1882.37   285.9 1891.26   294.2 1893.99   329.6 1901.73   348.6 1904.98
#Mann= 3 ,-1,0
       0      .1       0  118.37    .045       0   146.2      .1       0
#XS Ineff= 2 , 0
          110.05 1878.76
Permanent Ineff=
       F       F
Bank Sta=118.37,146.2
XS Rating Curve= 0 ,0
Exp/Cntr(USF)=0,0
Exp/Cntr=0.3,0.1