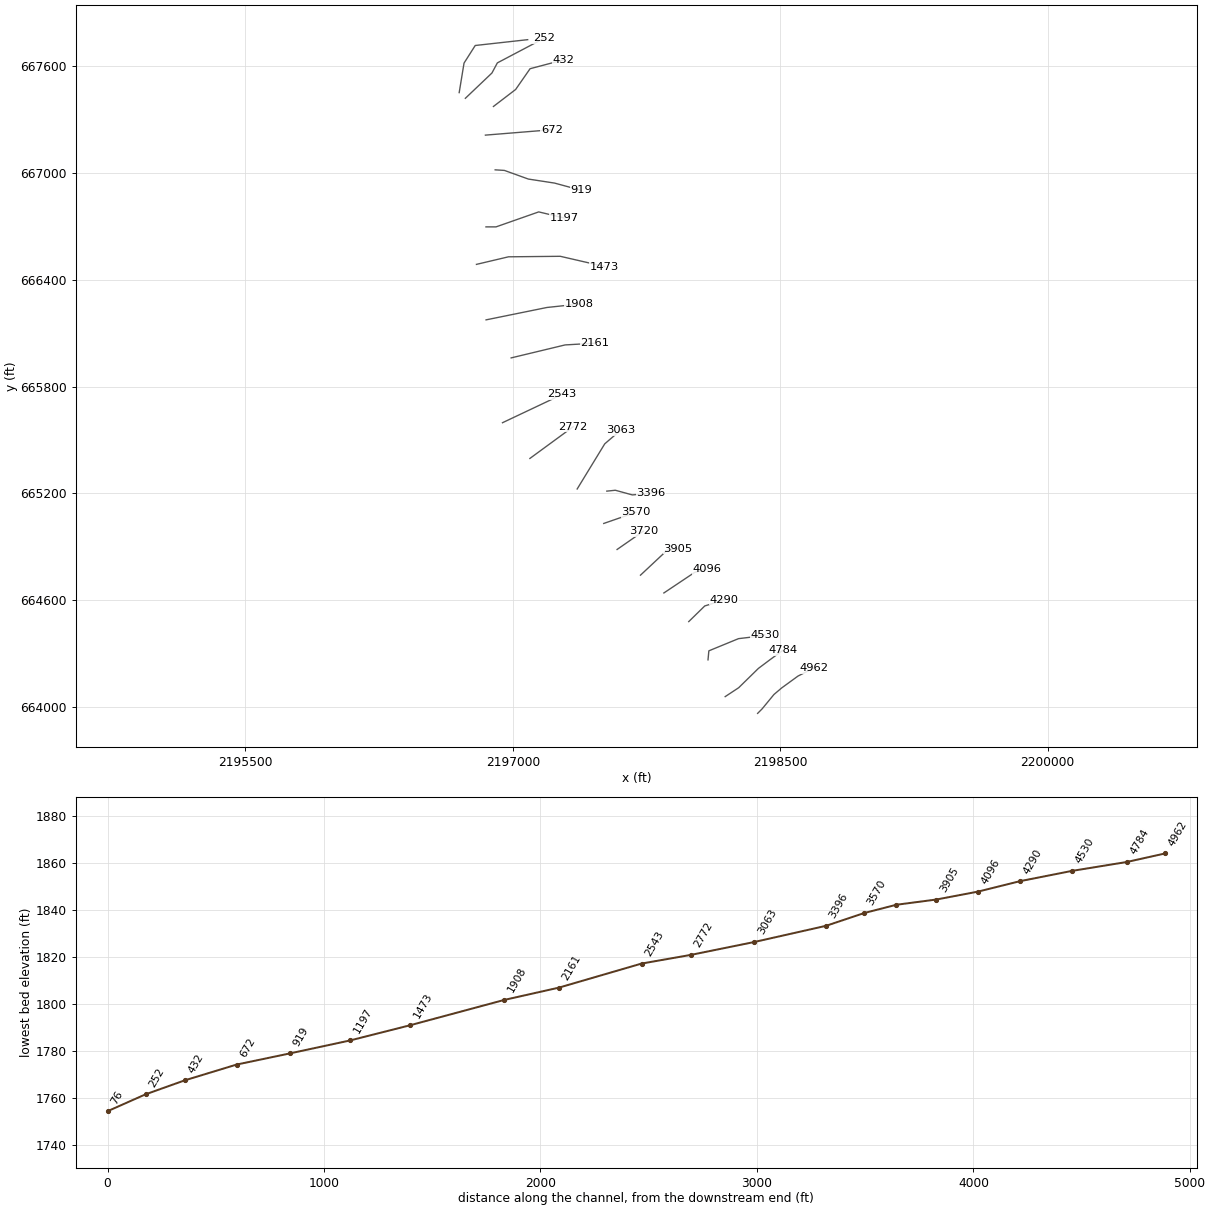
HEC-RAS study PANTHERCK.prj: PANTHERCK

--- PANTHERCK.g01 (geometry) --- (continued)

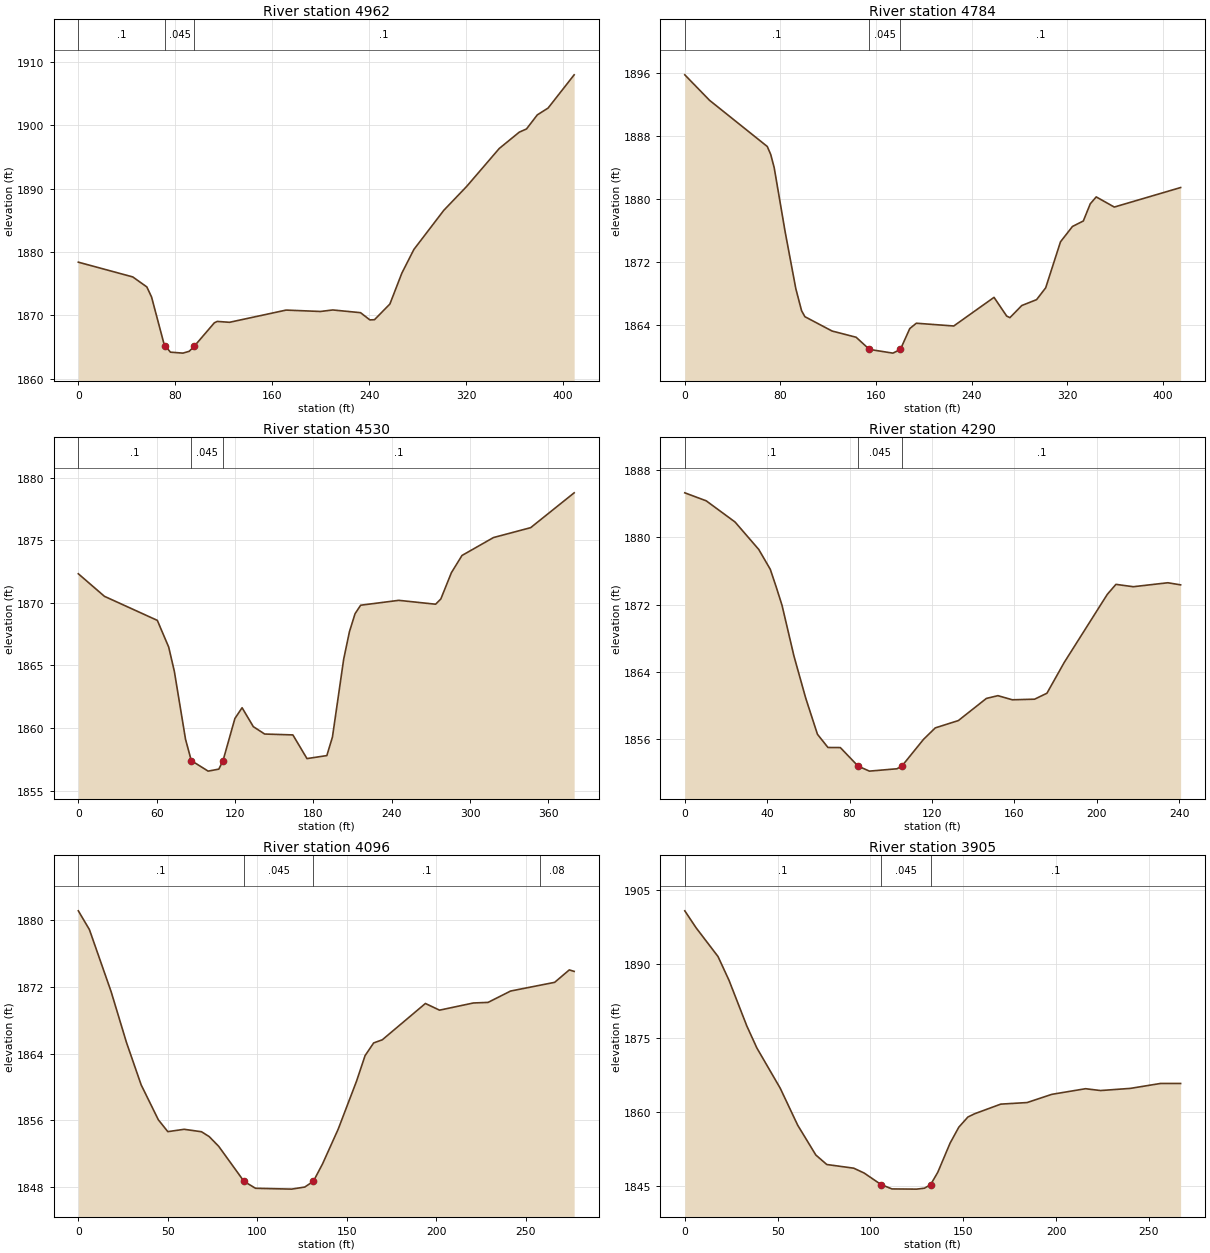
Type RM Length L Ch R = 1 ,4962    ,178.4,178.3,176.1
XS GIS Cut Line= 6
2198372.82485677663964.8140563362198397.72043624663989.709635799
2198464.54541269664070.9478424692198507.78510334664107.636064836
2198599.50565925 664174.46104129 2198687.2953342664219.011025593
#Sta/Elev= 30
       0 1878.39    44.9 1876.06    56.5 1874.48    60.4 1872.89    70.7 1865.46
    71.8 1865.11      76 1864.17    86.3 1864.02    91.5 1864.31   95.68 1865.12
   112.2 1868.81   114.6 1869.03   124.7 1868.89   171.4 1870.82   199.7  1870.6
   209.9 1870.84   232.8 1870.41   240.5 1869.27   244.3  1869.3     257 1871.78
   266.9 1876.67   276.8  1880.4   301.5 1886.59   320.3 1890.35   347.2 1896.35
   363.7 1898.93   369.7 1899.44   378.6 1901.66   387.5 1902.74     409 1907.99
#Mann= 3 ,-1,0
       0      .1       0    71.8    .045       0   95.68      .1       0
Bank Sta=71.8,95.68
XS Rating Curve= 0 ,0
Exp/Cntr(USF)=0,0
Exp/Cntr=0.3,0.1

Type RM Length L Ch R = 1 ,4784    ,260.4,254.2,251.5
XS GIS Cut Line= 5
2198190.89411214664058.8927410022198266.62429726664108.876713927
2198377.62487324664217.638322736 2198443.6636735664267.167422932
2198513.24026663664317.875787418
#Sta/Elev= 30
       0 1895.75    20.7 1892.51      69 1886.64    71.9 1885.62    74.8 1883.94
      84 1875.75    92.9 1868.55    97.7 1865.76   100.5    1865   123.2 1863.18
   143.3 1862.39   154.5 1860.84   174.1 1860.37  180.37 1860.84   188.2 1863.49
   193.7 1864.17     225 1863.82   258.7 1867.46   269.3 1865.08     272 1864.88
   281.9 1866.42   294.3 1867.17   301.9 1868.67   314.3 1874.52   324.3 1876.47
   333.4 1877.17   339.2 1879.35   344.2 1880.23   359.3 1878.94   414.8 1881.42
#Mann= 3 ,-1,0
       0      .1       0   154.5    .045       0  180.37      .1       0
Bank Sta=154.5,180.37
XS Rating Curve= 0 ,0
Exp/Cntr(USF)=0,0
Exp/Cntr=0.3,0.1

Type RM Length L Ch R = 1 ,4530    ,234.1,239.6,242.4
XS GIS Cut Line= 5
2198094.59750927664265.3089468262198099.31456643664316.017311311
2198265.59083138664384.4146401532198354.03565315664395.028018766
2198412.99886767 664405.64139738
#Sta/Elev= 30
       0 1872.32      20 1870.52    60.5  1868.6    69.2 1866.47    73.5 1864.55
    82.1 1859.11    86.5 1857.41    99.4 1856.57   107.6 1856.73  110.78  1857.4
   119.9 1860.77   125.4 1861.63     134 1860.12   142.7 1859.53   164.3 1859.46
   175.1 1857.57   190.3 1857.81   194.6 1859.29   203.2  1865.5   207.6 1867.69
   211.9 1869.13   216.2 1869.81   245.4  1870.2   273.6 1869.89   277.6 1870.31
   285.7 1872.41   293.8 1873.78   317.9 1875.21   346.4    1876   379.7 1878.78
#Mann= 3 ,-1,0
       0      .1       0    86.5    .045       0  110.78      .1       0
Bank Sta=86.5,110.78
XS Rating Curve= 0 ,0
Exp/Cntr(USF)=0,0
Exp/Cntr=0.3,0.1

Type RM Length L Ch R = 1 ,4290    ,197.2,194.3,192.6
XS GIS Cut Line= 3
2197986.53378758664480.1201594622198076.32297065 664567.99893438
 2198186.1714393664602.386281087
#Sta/Elev= 30
       0 1885.29    10.4 1884.34    24.4 1881.82    35.9 1878.56    41.5  1876.2
    44.3 1874.16    47.2 1871.92      53 1865.88    58.7 1860.89    64.4 1856.59
    69.5 1855.02    75.5 1855.01    84.11852.813    89.6 1852.21     103 1852.49
   105.41852.813   115.9 1855.99   121.6 1857.35   132.8 1858.22   146.4 1860.85
     152 1861.18     159 1860.69   169.8 1860.76   175.8 1861.47   184.2 1865.13
   205.1 1873.22   209.3 1874.41   217.7 1874.13   234.5  1874.6   240.7 1874.35
#Mann= 3 ,-1,0
       0      .1       0    84.1    .045       0   105.4      .1       0
Bank Sta=84.1,105.4
XS Rating Curve= 0 ,0
Exp/Cntr(USF)=0,0
Exp/Cntr=0.3,0.1

Type RM Length L Ch R = 1 ,4096    ,181.9,191,190.9
XS GIS Cut Line= 3
2197847.01999276664640.9727447112198019.83520432664756.593163974
2198086.69948958664773.786837328
#Sta/Elev= 30
       0 1881.08     6.2 1878.83    18.3 1871.42    26.9 1865.32    35.1 1860.25
    44.7 1856.07      50 1854.65    59.1 1854.93    68.8 1854.64    73.1 1854.06
    78.4  1852.9   92.56  1848.7      99 1847.87   119.2 1847.77   126.5 1848.02
   131.3  1848.7   136.5 1850.82   145.2 1854.96   155.4 1860.68   160.2 1863.75
     165 1865.27   169.8 1865.64   193.9 1869.99   201.8 1869.19   220.7 1870.05
   228.9 1870.12   241.5 1871.48   266.1 1872.52   274.3 1874.01     277 1873.83
#Mann= 4 ,-1,0
       0      .1       0   92.56    .045       0   131.3      .1       0
  257.93     .08       0
Bank Sta=92.56,131.3
XS Rating Curve= 0 ,0
Exp/Cntr(USF)=0,0
Exp/Cntr=0.3,0.1

Type RM Length L Ch R = 1 ,3905    ,185.8,185.5,185.7
XS GIS Cut Line= 3
2197715.82800742664740.9268718872197865.79504723664881.341870942
2197926.92810804664888.983503543
#Sta/Elev= 30
       0 1900.76     6.1 1897.32    17.9 1891.51    23.8 1886.72    33.4 1877.47
    38.8 1873.02    51.4 1864.87    60.8 1857.39    70.6 1851.34    76.5 1849.42
      91 1848.68    96.6  1847.7   105.7 1845.37   111.6 1844.48   124.9 1844.44
   129.1 1844.63  132.41 1845.34   136.3 1847.86   142.9 1853.74   147.6 1856.97
   152.5 1859.03   156.1 1859.69   170.2 1861.64   184.4 1861.96   197.7 1863.62
   215.9 1864.76     224 1864.39   240.1 1864.83   256.2 1865.82   267.1 1865.82
#Mann= 3 ,-1,0
       0      .1       0   105.7    .045       0  132.41      .1       0
Bank Sta=105.7,132.41
XS Rating Curve= 0 ,0
Exp/Cntr(USF)=0,0
Exp/Cntr=0.3,0.1

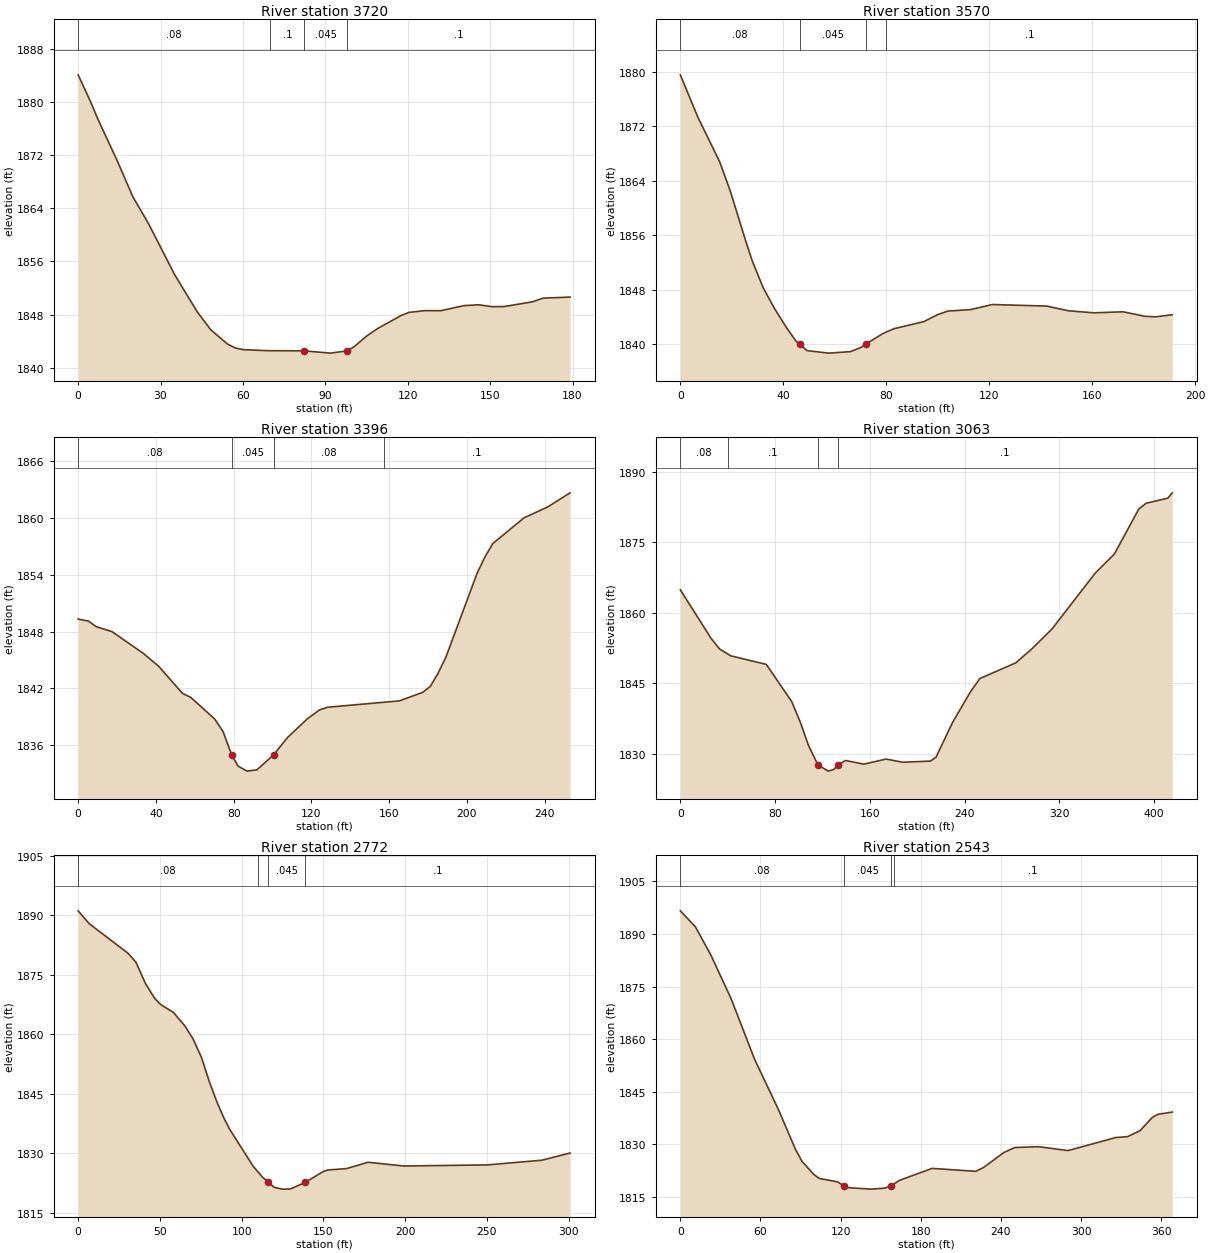
Type RM Length L Ch R = 1 ,3720    ,153.6,149.6,145.3
XS GIS Cut Line= 2
2197584.51878089664885.1176115232197731.52468807664987.419967977
#Sta/Elev= 30
       0 1884.06     4.5 1880.05     7.1 1877.48    14.2 1871.17    19.9 1865.74
    25.7 1861.62    35.1 1854.03    43.4 1848.39    48.3 1845.71    54.4 1843.56
    57.3 1842.96    60.1 1842.73    68.8 1842.57    82.4 1842.54    91.8  1842.2
   97.98 1842.54   100.4 1843.13   105.1 1844.79     109 1845.89   117.6 1847.86
   120.5 1848.33   126.2 1848.59     132 1848.58   140.6 1849.35   145.8 1849.47
   150.7 1849.19     155  1849.2   165.3 1849.91   169.3 1850.47   179.1 1850.63
#Mann= 4 ,-1,0
       0     .08       0      70      .1       0    82.4    .045       0
   97.98      .1       0
Bank Sta=82.4,97.98
XS Rating Curve= 0 ,0
Exp/Cntr(USF)=0,0
Exp/Cntr=0.3,0.1

Type RM Length L Ch R = 1 ,3570    ,181.9,174.2,165.2
XS GIS Cut Line= 3
2197509.72630181665031.2638350292197633.52074995665074.248018413
2197690.25987202665094.020742769
#Sta/Elev= 30
       0 1879.54     6.8 1873.33    15.3 1866.76    19.5 1862.37    25.4 1855.14
      28 1852.16    32.2 1848.26    36.5 1845.27    41.1 1842.49    44.9 1840.44
    46.3 1839.99    49.2 1839.03    57.6 1838.66    66.1 1838.88    70.3 1839.52
   71.99 1839.97    78.7 1841.54      83 1842.25    94.6 1843.29     100 1844.32
     104 1844.84   112.7 1845.05   121.2  1845.8   142.3 1845.57   150.8 1844.88
   160.6 1844.58     172 1844.73   180.5 1844.07   184.7 1843.99   191.1  1844.3
#Mann= 4 ,-1,0
       0     .08       0    46.3    .045       0   71.99     .08       0
      80      .1       0
Bank Sta=46.3,71.99
XS Rating Curve= 0 ,0
Exp/Cntr(USF)=0,0
Exp/Cntr=0.3,0.1

Type RM Length L Ch R = 1 ,3396    ,320.8,332.5,348.6
XS GIS Cut Line= 4
 2197526.9020457 665212.734526392197574.68457864665217.707618191
2197670.41849686665191.4264070032197775.70567501665201.453757303
#Sta/Elev= 30
       0 1849.32     5.3 1849.11     9.3 1848.52    17.4    1848    33.5 1845.71
    41.5 1844.33    53.7 1841.48    57.9 1841.07    70.3 1838.77    74.5 1837.48
      79    1835    82.2 1833.82    86.9 1833.28      92 1833.42  100.54 1834.99
   107.7 1836.82     118 1838.81   124.2 1839.74   128.4 1840.02   165.2 1840.69
   177.2 1841.58   181.2 1842.22   185.2 1843.61   189.3 1845.35   205.3 1854.17
   209.2 1855.83   213.4  1857.3   229.4    1860   241.5 1861.14   253.1 1862.64
#Mann= 4 ,-1,0
       0     .08       0      79    .045       0  100.54     .08       0
  157.32      .1       0
Bank Sta=79,100.54
XS Rating Curve= 0 ,0
Exp/Cntr(USF)=0,0
Exp/Cntr=0.3,0.1

Type RM Length L Ch R = 1 ,3063    ,291.8,291.3,281.9
XS GIS Cut Line= 3
2197360.70914889665224.8802388772197515.28425783665478.311522129
2197605.15350721665555.599076596
#Sta/Elev= 30
       0  1864.9      26 1854.58    33.1 1852.34    42.5 1850.88    72.6 1849.05
    94.1 1841.15   101.7 1836.54   108.1 1831.92   116.2 1827.69     125 1826.38
   129.6 1826.74  133.32 1827.71   139.5 1828.64     155 1827.86   173.7 1828.94
   187.8 1828.27   211.2 1828.51   215.9 1829.33   229.9 1836.72   244.8 1843.15
     253 1846.06   283.2 1849.37   296.9 1852.36   313.9 1856.59   350.3 1868.42
   366.6 1872.53   387.1 1882.04   393.3 1883.28   411.7 1884.37   415.4  1885.5
#Mann= 4 ,-1,0
       0     .08       0      40      .1       0   116.2    .045       0
  133.32      .1       0
Bank Sta=116.2,133.32
XS Rating Curve= 0 ,0
Exp/Cntr(USF)=0,0
Exp/Cntr=0.3,0.1

Type RM Length L Ch R = 1 ,2772    ,232.4,229.1,225.9
XS GIS Cut Line= 2
2197095.51459257 665396.35799466 2197338.1615659665574.299108433
#Sta/Elev= 30
       0 1891.09     6.8 1887.84    30.6 1880.37    35.4 1878.11    41.1 1872.83
    46.8 1869.04    50.4 1867.49    58.3 1865.48    65.3 1862.07    70.3 1858.79
    75.5 1854.08    80.2 1848.09    85.1 1842.69    89.3 1838.73    92.6 1836.09
   106.9  1826.8   112.7 1823.97   116.4 1822.69   119.9  1821.4   124.8 1820.94
   129.8 1820.97  139.02 1822.66   149.9 1825.37   152.7 1825.76   164.2 1826.12
   177.3 1827.71   199.2 1826.77     250 1827.04   283.6 1828.22   300.9 1830.04
#Mann= 4 ,-1,0
       0     .08       0     110      .1       0   116.4    .045       0
  139.02      .1       0
Bank Sta=116.4,139.02
XS Rating Curve= 0 ,0
Exp/Cntr(USF)=0,0
Exp/Cntr=0.3,0.1

Type RM Length L Ch R = 1 ,2543    ,382.5,381.9,368.9
XS GIS Cut Line= 3
2196941.83817613665596.9461592772197218.45572573665727.975524873
2197273.45570635665757.093161672
#Sta/Elev= 30
       0  1896.6    11.4 1891.99      23 1883.88      38 1871.57    55.7 1854.18
    73.4 1839.97      86 1828.75    91.1 1825.15     100  1821.4     104 1820.28
   117.7 1819.31   122.2 1818.24   126.5 1817.61   143.1 1817.23   153.1 1817.51
   158.1 1818.24   164.1 1819.74   188.5 1823.14   221.2 1822.31   227.2 1823.45
   242.2 1827.67   250.4 1829.09   268.1 1829.34   290.3 1828.22     326 1831.94
   334.9  1832.2   344.2 1833.91   353.3 1837.66   357.8 1838.58   368.3 1839.21
#Mann= 4 ,-1,0
       0     .08       0   122.2    .045       0   158.1     .08       0
     160      .1       0
Bank Sta=122.2,158.1
XS Rating Curve= 0 ,0
Exp/Cntr(USF)=0,0
Exp/Cntr=0.3,0.1

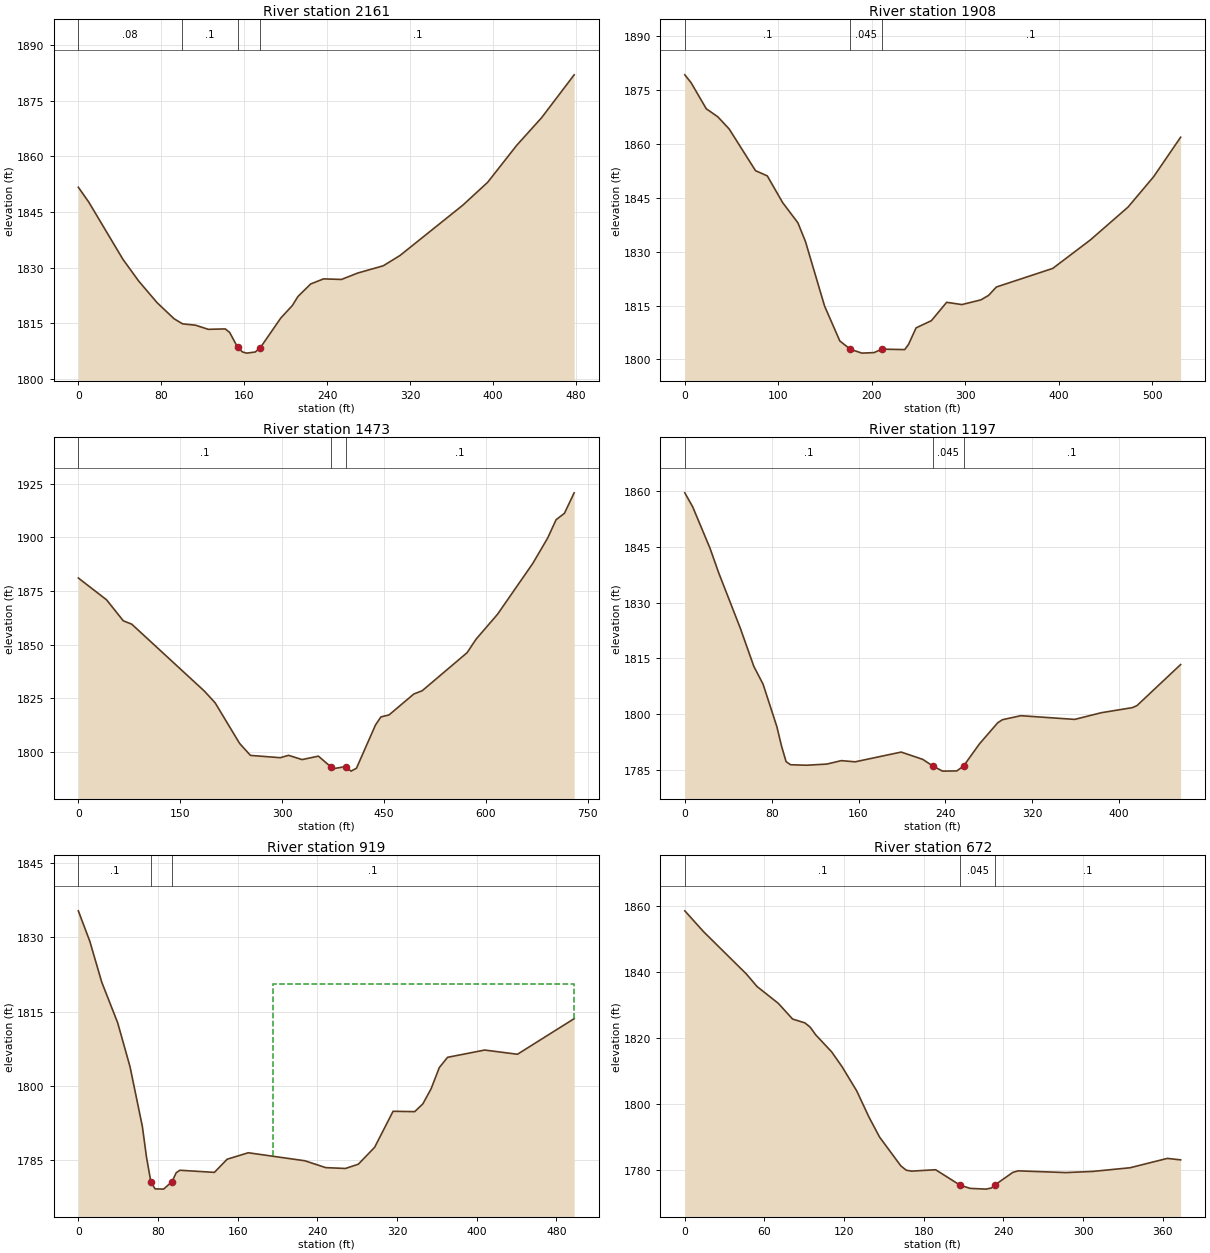
Type RM Length L Ch R = 1 ,2161    ,248.6,253.1,244.2
XS GIS Cut Line= 3
 2196990.3675708665960.9166192672197292.86746421666033.710711265
2197459.48505256666043.416590198
#Sta/Elev= 30
       0  1851.7    10.1 1847.68      43 1832.28    58.1 1826.46    75.9 1820.61
    92.4 1816.25   100.6 1814.89   112.9 1814.54   125.3 1813.42   141.7 1813.53
   145.9 1812.58  153.63 1808.55   158.2 1807.33   162.3 1807.01   170.5 1807.31
   175.5  1808.5   195.2 1816.47   206.3 1819.83   211.7 1822.26     224 1825.64
   236.4 1827.01   253.7 1826.86   269.3 1828.58     294 1830.54   310.1 1833.31
   370.6 1846.85   394.6 1853.02   422.6 1862.98   446.7 1870.46     478 1881.98
#Mann= 4 ,-1,0
       0     .08       0     100      .1       0  153.63    .045       0
   175.5      .1       0
Bank Sta=153.63,175.5
XS Rating Curve= 0 ,0
Exp/Cntr(USF)=0,0
Exp/Cntr=0.3,0.1

Type RM Length L Ch R = 1 ,1908    ,433.2,435.2,415.2
XS GIS Cut Line= 3
2196849.63232627666174.4459557952197190.95573542666244.004754815
2197372.13214217666263.416512681
#Sta/Elev= 30
       0 1879.15     6.7 1876.98      23 1869.71    35.3 1867.49    47.5 1864.09
    75.7  1852.5    88.3 1851.05   104.7 1843.63     121 1838.02   129.1 1832.82
   149.6 1814.85   165.9 1805.15   177.1 1802.86   189.5 1801.77   202.6 1801.92
   210.8 1802.88   235.3 1802.75   239.4 1804.19   247.5 1808.79   263.9  1810.8
   280.2  1815.9   296.5 1815.27   316.9 1816.58   325.1 1817.83   333.4 1820.15
   393.8 1825.33   434.1 1833.26   474.3 1842.37   501.6 1850.78   530.6  1861.8
#Mann= 3 ,-1,0
       0      .1       0   177.1    .045       0   210.8      .1       0
Bank Sta=177.1,210.8
XS Rating Curve= 0 ,0
Exp/Cntr(USF)=0,0
Exp/Cntr=0.3,0.1

Type RM Length L Ch R = 1 ,1473    ,270.3,276.2,275.1
XS GIS Cut Line= 4
2196795.70279146666486.0219161232196975.41811636666528.516126383
2197265.80015522666531.3817386082197514.15321477666474.069494096
#Sta/Elev= 30
       0 1881.05    41.6 1870.87    66.2 1861.09    78.6 1859.54   185.4 1828.37
   201.4 1822.86   237.4 1803.94   253.4 1798.34   297.4 1797.27   309.4 1798.39
   329.4 1796.39   353.4    1798  371.32 1793.11   377.4 1792.26   393.4 1793.13
   401.4 1791.01   409.4 1792.34   437.4 1812.49   445.4 1816.28   457.4 1817.22
   493.9 1826.97   506.2 1828.49   572.3 1846.23   585.6 1852.56   617.1 1864.14
     669 1887.85     691 1899.74   703.3 1908.22   715.6 1911.22   729.9 1920.76
#Mann= 3 ,-1,0
       0      .1       0  371.32    .045       0   393.4      .1       0
Bank Sta=371.32,393.4
XS Rating Curve= 0 ,0
Exp/Cntr(USF)=0,0
Exp/Cntr=0.3,0.1

Type RM Length L Ch R = 1 ,1197    ,284,277.7,270.8
XS GIS Cut Line= 4
2196848.95859301666696.5862180152196905.57622012666696.586218015
2197144.98790047666780.7038354372197287.34079149 666746.73325917
#Sta/Elev= 30
       0 1859.63     7.2  1855.9    23.2 1844.71    31.2 1838.08    51.2 1823.08
    63.6 1812.82    72.1 1808.03    84.8 1796.58    89.1 1791.35    93.3 1787.13
    97.5  1786.3   112.2 1786.17   130.8 1786.48   144.2 1787.41   156.9 1787.09
   199.3 1789.72   219.1 1787.76   228.5 1785.96   237.4 1784.58   250.5 1784.63
   256.8 1785.96   271.4 1791.93   288.3 1797.64   292.6 1798.45   309.5 1799.53
   359.1 1798.53   383.6 1800.33   412.2  1801.7   416.5 1802.25   456.7 1813.32
#Mann= 3 ,-1,0
       0      .1       0   228.5    .045       0   256.8      .1       0
Bank Sta=228.5,256.8
XS Rating Curve= 0 ,0
Exp/Cntr(USF)=0,0
Exp/Cntr=0.3,0.1

Type RM Length L Ch R = 1 ,919     ,240.8,246.7,252.1
XS GIS Cut Line= 5
2196900.72328065667016.880222812 2196952.4879683667013.644929835
2197086.75262687666965.1155351682197233.95845736666942.468484324
2197382.78193434666902.027322102
#Sta/Elev= 30
       0 1835.39    11.5 1829.25    23.5 1820.96    39.5 1812.74    51.9 1803.85
    64.3 1791.74    68.5 1785.47    72.8  1780.6      77 1779.14    85.6 1779.08
    94.1 1780.61    98.3 1782.41     102  1782.9   136.6 1782.47   149.4 1785.13
   170.6 1786.44   227.4 1784.82   248.4 1783.43   268.2 1783.26   281.1 1784.12
   297.5 1787.55     316 1794.83   337.7 1794.76   345.9 1796.33   354.2  1799.4
   362.4 1803.67   370.7 1805.75     408 1807.22   440.9 1806.37   497.8 1813.57
#Mann= 3 ,-1,0
       0      .1       0    72.8    .045       0    94.1      .1       0
#XS Ineff= 2 , 0
                          195.77         1820.57
Permanent Ineff=
       F       F
Bank Sta=72.8,94.1
XS Rating Curve= 0 ,0
Exp/Cntr(USF)=0,0
Exp/Cntr=0.3,0.1

Type RM Length L Ch R = 1 ,672     ,232.2,239.9,245.8
XS GIS Cut Line= 2
2196845.97189588667211.8133203632197218.14146947667242.092561763
#Sta/Elev= 30
       0 1858.58    14.2 1852.24    46.4 1839.45    54.4 1835.67    70.4 1830.58
    81.2 1825.81    90.5 1824.65    94.5 1823.33    98.5 1821.08   110.6 1815.88
   118.4 1811.41   129.5 1804.05   138.7 1796.14   146.7 1790.08   162.7 1781.37
   166.8 1780.05   170.8 1779.78   188.9  1780.2   207.4 1775.51   214.9 1774.56
     227 1774.33     231 1774.69   233.4 1775.55     247 1779.39     251 1779.86
   287.1 1779.34   307.2 1779.69   335.3  1780.8   363.4 1783.63   373.4 1783.19
#Mann= 3 ,-1,0
       0      .1       0   207.4    .045       0   233.4      .1       0
Bank Sta=207.4,233.4
XS Rating Curve= 0 ,0
Exp/Cntr(USF)=0,0
Exp/Cntr=0.3,0.1

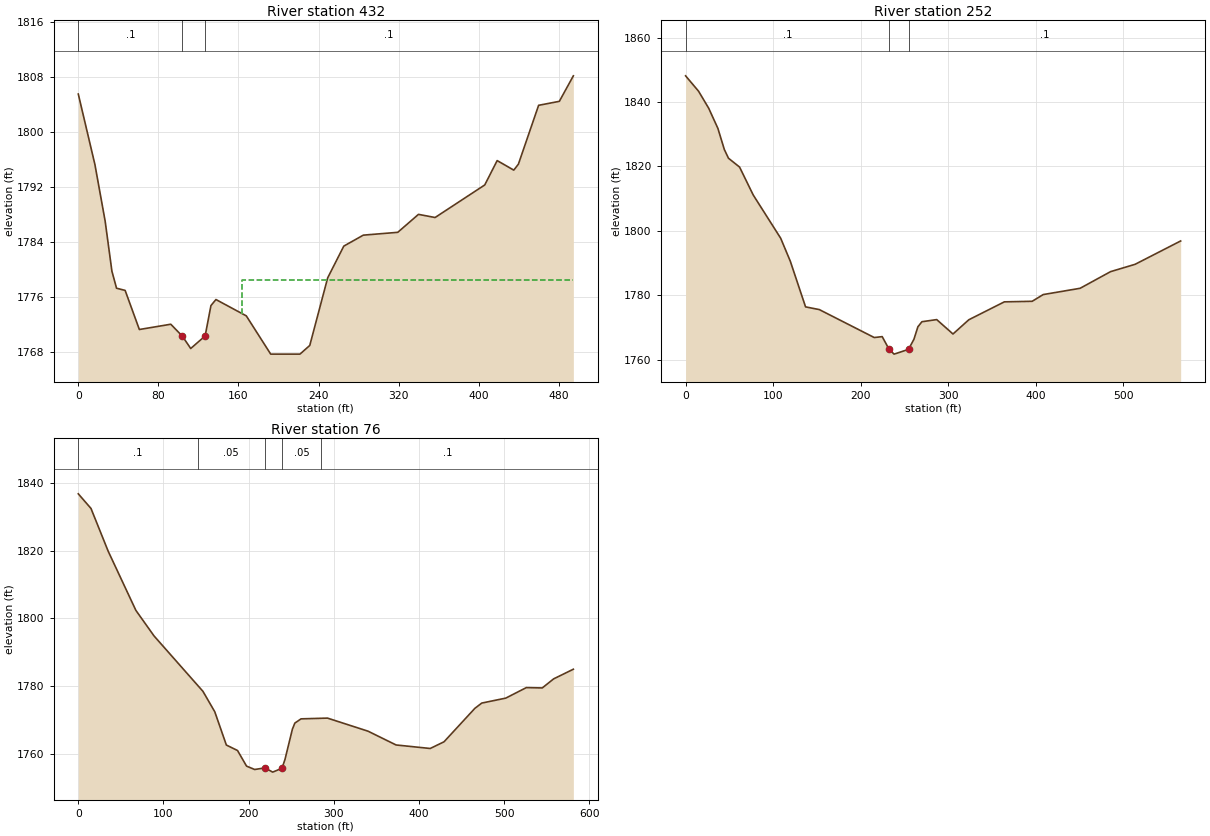
Type RM Length L Ch R = 1 ,432     ,175,180.3,183.5
XS GIS Cut Line= 4
2196891.01740172667372.7624503652197015.57618136667468.203593208
2197096.45850581667584.674140407  2197285.723145667634.821181562
#Sta/Elev= 30
       0 1805.54    16.6 1795.27    26.8 1787.04    33.6  1779.7    38.2 1777.23
    46.8 1776.91      61 1771.21    92.4 1771.98  103.98 1770.23   112.3 1768.44
   126.7 1770.27   132.5  1774.7   137.5 1775.58   167.8  1773.2   192.2 1767.62
   221.4 1767.62   231.2 1768.88   249.1 1778.74   265.2 1783.37   284.7 1784.97
   319.1 1785.38   339.8    1788   356.4 1787.54     406 1792.29   418.4 1795.84
     435 1794.45   439.6 1795.32   459.8  1803.9   480.5 1804.48   494.5  1808.2
#Mann= 3 ,-1,0
       0      .1       0  103.98    .045       0   126.7      .1       0
#XS Ineff= 2 , 0
                           163.8         1778.37
Permanent Ineff=
       F       F
Bank Sta=103.98,126.7
XS Rating Curve= 0 ,0
Exp/Cntr(USF)=0,0
Exp/Cntr=0.3,0.1

Type RM Length L Ch R = 1 ,252     ,174.8,176.2,171.7
XS GIS Cut Line= 4
2196733.46086676667418.6263592552196882.50793928 667560.49056181
2196912.94671957667617.4137892472197174.32639778667755.296574203
#Sta/Elev= 30
       0 1848.11    14.8 1843.34    26.4 1838.05    36.9  1831.8    44.3 1825.22
      49 1822.53    61.7 1819.78    77.3 1811.11   108.7 1797.68   119.7 1790.53
   137.1 1776.38   152.8 1775.54   215.6 1766.86   224.7 1767.14   232.6 1763.18
   238.3 1761.71   254.8 1763.19     261 1766.36   265.5 1770.21   270.1 1771.77
     287 1772.43   305.6 1767.96   323.7 1772.38   364.3 1777.94   396.1 1778.11
   408.7  1780.2   450.9 1782.15   485.7 1787.32   513.7 1789.59   565.8 1796.84
#Mann= 3 ,-1,0
       0      .1       0   232.6    .045       0   254.8      .1       0
Bank Sta=232.6,254.8
XS Rating Curve= 0 ,0
Exp/Cntr(USF)=0,0
Exp/Cntr=0.3,0.1

Type RM Length L Ch R = 1 ,76      ,,,
XS GIS Cut Line= 4
2196698.85200592667450.4954282932196726.04488711667616.267415554
2196788.79768985667715.1030798822197083.03503157 667747.81196917
#Sta/Elev= 30
       0 1836.89    14.9 1832.56    35.1  1819.9    67.6 1802.39    88.9 1794.83
   146.3 1778.43   160.2 1772.38   173.8 1762.53   186.9 1760.91   197.5 1756.29
     207 1755.29   219.11755.764   228.2 1754.51   239.1 1755.66   242.6 1758.25
   251.3 1767.22   254.2 1769.03   261.5 1770.28   292.5  1770.5   340.1 1766.63
     373 1762.55   413.1 1761.51   429.3 1763.49   465.5 1773.39   473.6 1774.95
   501.8 1776.42   525.9 1779.53   544.6 1779.43     558 1782.12   581.1 1784.97
#Mann= 5 ,-1,0
       0      .1       0     140     .05       0   219.1    .045       0
   239.1     .05       0  285.06      .1       0
Bank Sta=219.1,239.1
XS Rating Curve= 0 ,0
Exp/Cntr(USF)=0,0
Exp/Cntr=0.3,0.1
LCMann Table=0

Chan Stop Cuts=-1
Use User Specified Reach Order=0
Composite Channel Slope=5